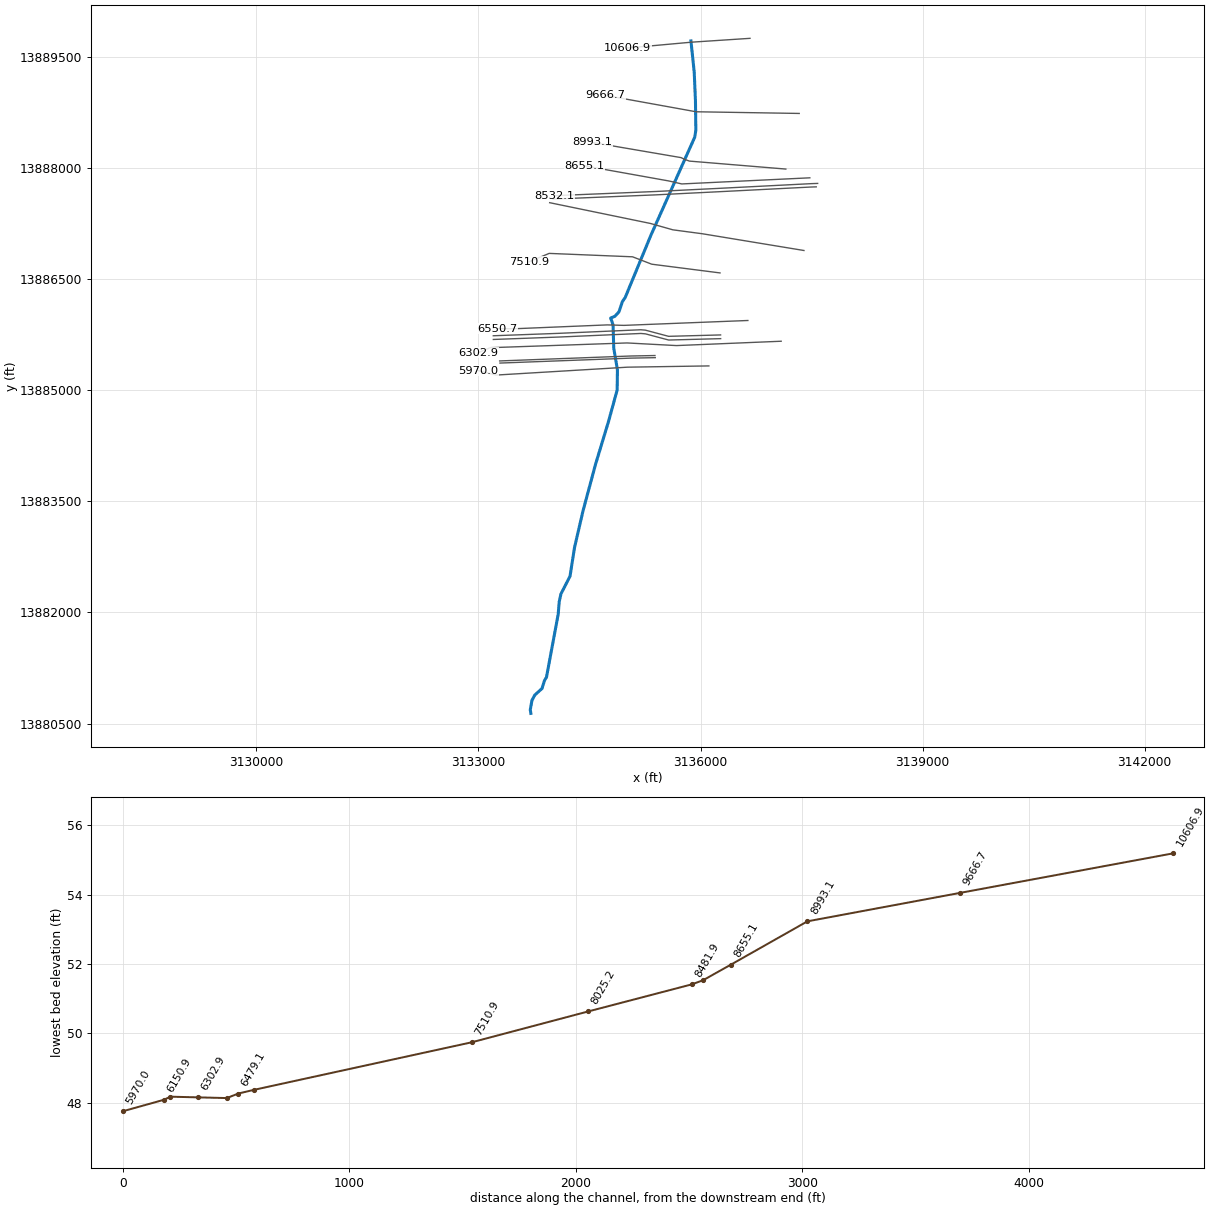
--- P118-14-00.PRJ (project) ---

Proj Title=P118-14-00
Current Plan=p02
Default Exp/Contr=.3,.1
English Units
Geom File=g01
Flow File=f01
Flow File=f02
Plan File=p01
Plan File=p02
Y Axis Title=Elevation
X Axis Title(PF)=Main Channel Distance
X Axis Title(XS)=Station
BEGIN DESCRIPTION:
Greens/Halls Bayou Watershed
Tributary 6.71 to Halls Bayou
HCFCD Unit P118-14-00
Flood Hazard Model
10, 2, 1, 0.2% Event
Filename P118-14-00.prj
Prepared by:  Watershed Concepts  Date:
Reviewed by:                      Date:
STATUS FINAL
END DESCRIPTION:
DSS Export Rating Curves= 0
DSS Export Rating Curve Sorted= 0
DSS Export Volume Flow Curves= 0
DXF OffsetX= 0
DXF OffsetY= 0
DXF ScaleX= 1
DXF ScaleY= 10

--- P118-14-00.p02 (plan) ---

Plan Title=Floodway
Version=Version 3.0.1  Mar 2001
Short Identifier=Floodway0607
Geom File=g01
Flow File=f02
Subcritical Flow
K Sum by GR= 0
Std Step Tol= 0.01
Critical Tol= 0.01
Num of Std Step Trials= 20
Max Error Tol= 0.3
Flow Tol Ratio= 0.001
Split Flow NTrial= 30
Split Flow Tol= 0.02
Split Flow Ratio= 0.02
Log Output Level= 0
Friction Slope Method= 1
Unsteady Friction Slope Method= 2
Parabolic Critical Depth
Global Vel Dist= 0 , 0 , 0
Global Log Level= 0
CheckData=True
Encroach Param=-1 ,0,0, 2
Encroach River=P118-14-00
Encroach Reach=Reach - 1
Encroach Node=10606.9
       1  4982.9  5043.5
Encroach Node=9666.7
       1  4982.9  5075.2
Encroach Node=8993.1
       1    4965    5090
Encroach Node=8655.1
       1    4970    5140
Encroach Node=8532.1
       1    4977    5420
Encroach Node=8507.0
       1    4977    5420
Encroach Node=8481.9
       1    4977    5420
Encroach Node=8025.2
       1    4875    5390
Encroach Node=7510.9
       1    4950    5420
Encroach Node=6550.7
       1    4950    5417
Encroach Node=6479.1
       1  4977.8    5457
Encroach Node=6454.1
       1  4977.8    5457
Encroach Node=6429.1
       1  4977.8    5457
Encroach Node=6302.9
       1    4945    5453
Encroach Node=6179.9
       1    4900    5450
Encroach Node=6165.4
       1    4900    5450
Encroach Node=6150.9
       1    4900    5450
Encroach Node=5970.0
       1    4900    5506
Encroach Node=5823.6
       1    4880    5480
Encroach Node=5800.1
       1    4880    5480
Encroach Node=5776.6
       1    4880    5480
Encroach Node=5628.5
       1    4900    5390
Encroach Node=5509.6
       1    4900    5340
Encroach Node=5484.6
       1    4900    5340
Encroach Node=5459.6
       1    4900    5340
Encroach Node=5294.4
       1    4900    5260
Encroach Node=5161.0
       1    4900    5215
Encroach Node=5136.0
       1    4900    5215
Encroach Node=5111.0
       1    4900    5215
Encroach Node=4683.7
       1    4900    5200
Encroach Node=4316.3
       1    4810    5200
Encroach Node=4164.8
       1    4800    5220
Encroach Node=4140.3
       1    4800    5220
Encroach Node=4115.8
       1    4800    5220
Encroach Node=3617.5
       1    4850    5340
Encroach Node=3259.8
       1    4850    6175
Encroach Node=3169.5
       1  4972.7    6200
Encroach Node=3141.3
       1  4972.7    6200
Encroach Node=3113.1
       1  4972.7    6200
Encroach Node=2974.8
       1    4850    6000
Encroach Node=2884.9
       1    4850    5875
Encroach Node=2836.2
       1  4959.1    5800
Encroach Node=2771.2
       1  4959.1    5800
Encroach Node=2706.2
       1  4959.1    5470
Encroach Node=2164.7
       1  4950.7    5565
Encroach Node=1654.8
       1    4900    5560
Encroach Node=1523.9
       1  4950.7    5520
Encroach Node=1492.9
       1  4950.7    5520
Encroach Node=1461.9
       1  4950.7    5520
Encroach Node=1132.9
       1    4930    5550
Encroach Reach=P118-14-00_0011
Encroach Node=10606.9
       1  4982.9  5043.5
Encroach Node=9666.7
       1  4982.9  5075.2
Encroach Node=8993.1
       1    4965    5090
Encroach Node=8655.1
       1    4970    5140
Encroach Node=8532.1
       1    4977    5420
Encroach Node=8507.0
       1    4977    5420
Encroach Node=8481.9
       1    4977    5420
Encroach Node=8025.2
       1    4875    5390
Encroach Node=7510.9
       1    4950    5420
Encroach Node=6550.7
       1    4950    5417
Encroach Node=6479.1
       1  4977.8    5457
Encroach Node=6454.1
       1  4977.8    5457
Encroach Node=6429.1
       1  4977.8    5457
Encroach Node=6302.9
       1    4945    5453
Encroach Node=6179.9
       1    4900    5450
Encroach Node=6165.4
       1    4900    5450
Encroach Node=6150.9
       1    4900    5450
Encroach Node=5970.0
       1    4900    5506
Encroach Node=5823.6
       1    4880    5480
Encroach Node=5800.1
       1    4880    5480
Encroach Node=5776.6
       1    4880    5480
Encroach Node=5628.5
       1    4900    5390
Encroach Node=5509.6
       1    4900    5340
Encroach Node=5484.6
       1    4900    5340
Encroach Node=5459.6
       1    4900    5340
Encroach Node=5294.4
       1    4900    5260
Encroach Node=5161.0
       1    4900    5215
Encroach Node=5136.0
       1    4900    5215
Encroach Node=5111.0
       1    4900    5215
Encroach Node=4683.7
       1    4900    5200
Encroach Node=4316.3
       1    4810    5200
Encroach Node=4164.8
       1    4800    5220
Encroach Node=4140.3
       1    4800    5220
Encroach Node=4115.8
       1    4800    5220
Encroach Node=3617.5
       1    4850    5340
Encroach Node=3259.8
       1    4850    6175
Encroach Node=3169.5
       1  4972.7    6200
Encroach Node=3141.3
       1  4972.7    6200
Encroach Node=3113.1
       1  4972.7    6200
Encroach Node=2974.8
       1    4850    6000
Encroach Node=2884.9
       1    4850    5875
Encroach Node=2836.2
       1  4959.1    5800
Encroach Node=2771.2
       1  4959.1    5800
Encroach Node=2706.2
       1  4959.1    5470
Encroach Node=2164.7
       1  4950.7    5565
Encroach Node=1654.8
       1    4900    5560
Encroach Node=1523.9
       1  4950.7    5520
Encroach Node=1492.9
       1  4950.7    5520
Encroach Node=1461.9
       1  4950.7    5520
Encroach Node=1132.9
       1    4930    5550
Computation Interval=1HOUR
Output Interval=1HOUR
Run HTab= 0
Run UNet= 0
Run PostProcess= 0
UNET Theta= 1
UNET ZTol= 0.02
UNET ZSATol= 0.1
UNET MxIter= 20
UNET MaxInSteps= 20
UNET DtIC= 0
UNET DtMin= 0
UNET MaxCRTS= 20
UNET WFStab= 2
UNET SFStab= 1
UNET WFX= 1
UNET SFX= 1
UNET Convert EG Bridges=-1
UNET Use Existing IB Tables=-1
Instantaneous Interval=1HOUR
Write IC File= 0
Write Velocity= 0
Write Detailed= 0

--- P118-14-00.p01 (plan) ---

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Plan Title=FEMA Effective June 2007
Short Identifier=FEMAeff0607
Geom File=g01
Flow File=f01
Encroach Param=-1 ,0,0, 0
DSS File=dss

--- P118-14-00.f02 (steady flow) ---

Flow Title= Floodway
Number of Profiles= 2
Profile Names=1PCT_100yr, 1PCTFloodway_100yrFW
River Rch & RM=P118-14-00,P118-14-00_0011,10606.9
     899     899
River Rch & RM=P118-14-00,P118-14-00_0011,8532.1
     935     935
River Rch & RM=P118-14-00,P118-14-00_0011,8025.2
     977     977
River Rch & RM=P118-14-00,P118-14-00_0011,7510.9
    1060    1060
River Rch & RM=P118-14-00,P118-14-00_0011,6550.7
    1097    1097
River Rch & RM=P118-14-00,P118-14-00_0011,6179.9
    1114    1114
River Rch & RM=P118-14-00,P118-14-00_0011,5970
    1164    1164
River Rch & RM=P118-14-00,P118-14-00_0011,5509.6
    1199    1199
River Rch & RM=P118-14-00,P118-14-00_0011,5161
    1244    1244
River Rch & RM=P118-14-00,P118-14-00_0011,4683.7
    1306    1306
River Rch & RM=P118-14-00,P118-14-00_0011,4164.8
    1363    1363
River Rch & RM=P118-14-00,P118-14-00_0011,3617.5
    1423    1423
River Rch & RM=P118-14-00,P118-14-00_0011,2974.8
    1476    1476
River Rch & RM=P118-14-00,P118-14-00_0011,2164.7
    1612    1612
River Rch & RM=P118-14-00,P118-14-00_0011,1654.8
    1630    1630
River Rch & RM=P118-14-00,P118-14-00_0011,1523.9
    1698    1698
Boundary for River Rch & Prof#=P118-14-00,P118-14-00_0011, 1
Up Type= 0
Dn Type= 3
Dn Slope= 0.00200
Boundary for River Rch & Prof#=P118-14-00,P118-14-00_0011, 2
Up Type= 0
Dn Type= 3
Dn Slope= 0.00200

--- P118-14-00.f01 (steady flow) ---

Flow Title= FEMA Effective June 2007
Number of Profiles= 4
Profile Names=10PCT_10yr, 2PCT_50yr, 1PCT_100yr, 0.2PCT_500yr
River Rch & RM=P118-14-00,P118-14-00_0011,10606.9
     518     770     899    1274
River Rch & RM=P118-14-00,P118-14-00_0011,8532.1
     539     801     935    1325
River Rch & RM=P118-14-00,P118-14-00_0011,8025.2
     563     837     977    1385
River Rch & RM=P118-14-00,P118-14-00_0011,7510.9
     611     909    1060    1503
River Rch & RM=P118-14-00,P118-14-00_0011,6550.7
     633     941    1097    1555
River Rch & RM=P118-14-00,P118-14-00_0011,6179.9
     643     955    1114    1580
River Rch & RM=P118-14-00,P118-14-00_0011,5970
     671     998    1164    1650
River Rch & RM=P118-14-00,P118-14-00_0011,5509.6
     692    1028    1199    1700
River Rch & RM=P118-14-00,P118-14-00_0011,5161
     717    1066    1244    1763
River Rch & RM=P118-14-00,P118-14-00_0011,4683.7
     753    1119    1306    1851
River Rch & RM=P118-14-00,P118-14-00_0011,4164.8
     786    1168    1363    1932
River Rch & RM=P118-14-00,P118-14-00_0011,3617.5
     820    1220    1423    2017
River Rch & RM=P118-14-00,P118-14-00_0011,2974.8
     851    1265    1476    2092
River Rch & RM=P118-14-00,P118-14-00_0011,2164.7
     929    1382    1612    2285
River Rch & RM=P118-14-00,P118-14-00_0011,1654.8
     940    1397    1630    2311
River Rch & RM=P118-14-00,P118-14-00_0011,1523.9
     979    1455    1698    2407
Boundary for River Rch & Prof#=P118-14-00,P118-14-00_0011, 1
Up Type= 0
Dn Type= 3
Dn Slope= 0.00200
Boundary for River Rch & Prof#=P118-14-00,P118-14-00_0011, 2
Up Type= 0
Dn Type= 3
Dn Slope= 0.00200
Boundary for River Rch & Prof#=P118-14-00,P118-14-00_0011, 3
Up Type= 0
Dn Type= 3
Dn Slope= 0.00200
Boundary for River Rch & Prof#=P118-14-00,P118-14-00_0011, 4
Up Type= 0
Dn Type= 3
Dn Slope= 0.00200

--- P118-14-00.g01 (geometry) ---

Geom Title=P118-14-00 June 2007
Version=Version 3.0.1  Mar 2001

River Reach=P118-14-00      ,P118-14-00_0011
Reach XY= 30
        3135871.       13889710.      3135915.07     13889289.08
      3135931.96     13888898.28      3135936.78     13888505.07
      3135922.25       13888412.      3135330.75       13887090.
        3134983.       13886249.      3134945.66     13886194.18
      3134898.25       13886055.      3134844.75       13885996.
        3134786.       13885971.       3134818.5       13885882.
       3134828.5       13885562.      3134878.04     13885273.81
       3134874.5       13885002.      3134759.56     13884582.59
      3134582.25       13883998.        3134413.       13883369.
       3134298.5       13882876.      3134237.75       13882489.
      3134114.25       13882247.      3134091.25       13882142.
        3134078.       13881976.       3133919.5       13881125.
      3133893.34     13881082.67       3133858.5       13880972.
        3133763.       13880886.      3133723.45     13880813.81
      3133700.54     13880686.65      3133708.61     13880637.33

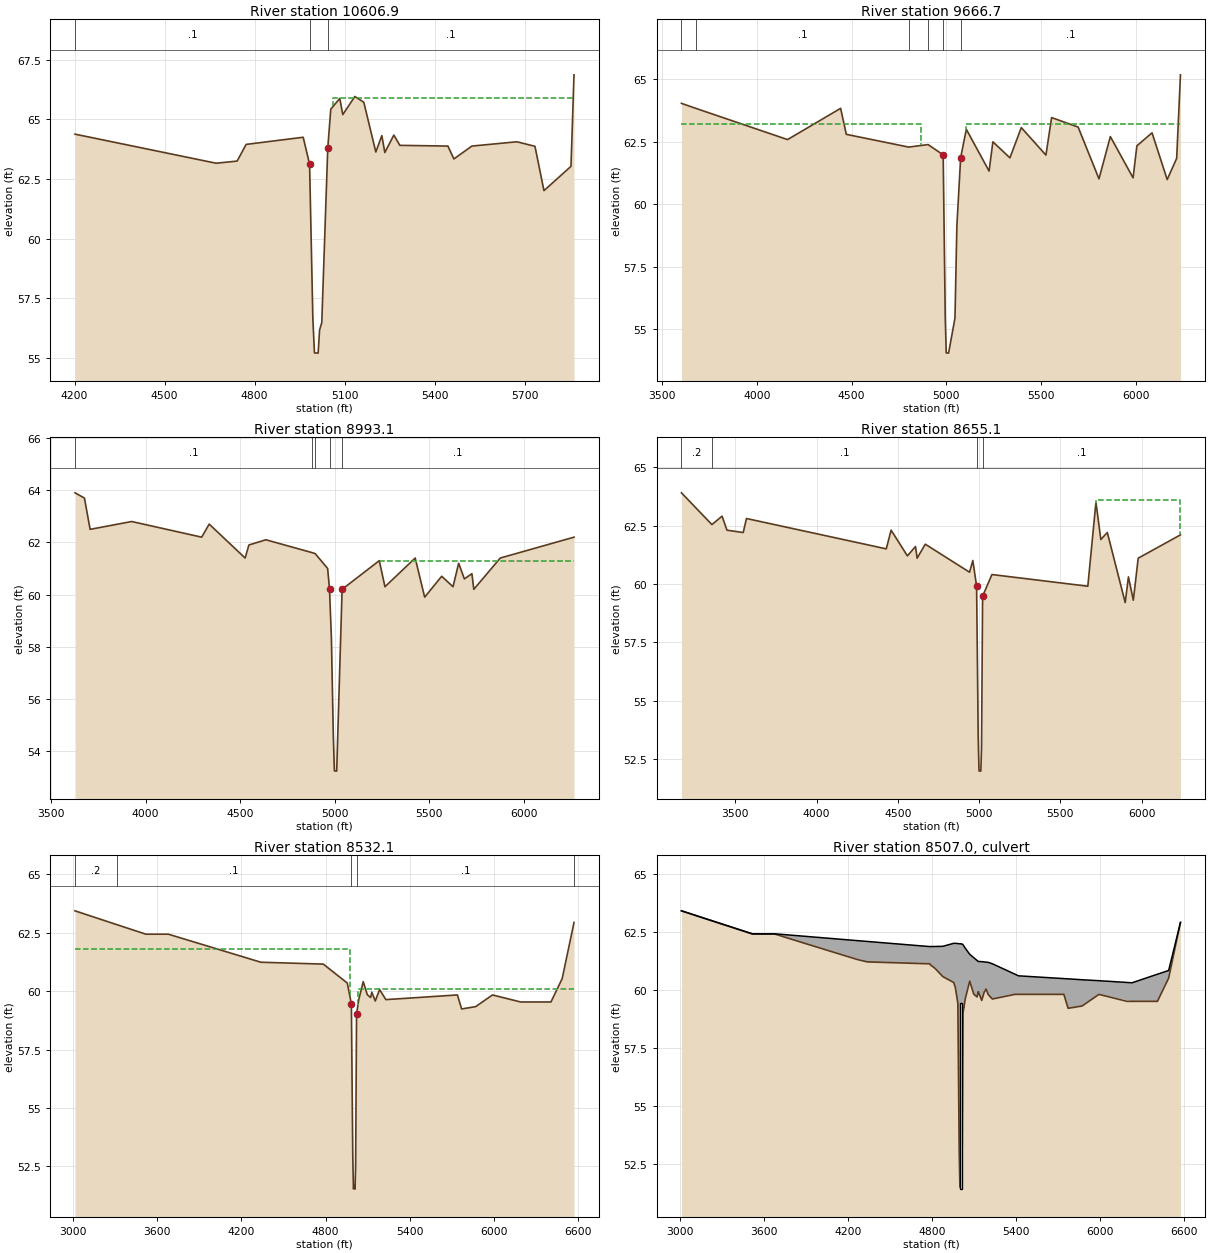
Type RM Length L Ch R = 1 ,10606.9 ,970.2,940.2,821.6
BEGIN DESCRIPTION:
Cross Section 10606.9-Interpolated
END DESCRIPTION:
XS GIS Cut Line= 3
      3136668.75     13889745.22      3135878.56      13889693.4
      3135012.12     13889614.64
#Sta/Elev= 30
  4201.6   64.38  4671.6   63.16  4741.6   63.25  4771.6   63.95  4961.6   64.25
  4982.9   63.12  4993.8   56.64  4999.1    55.2  5011.4   55.19  5016.2   56.16
  5023.5   56.47  5043.5    63.8  5053.5   65.43  5083.5   65.88  5093.5    65.2
  5133.5   65.96  5163.5   65.72  5203.5   63.63  5223.5   64.32  5233.5   63.61
  5263.5   64.34  5283.5   63.91  5443.5   63.88  5463.5   63.34  5523.5   63.88
  5673.5   64.06  5733.5   63.87  5763.5   62.01  5853.5   63.03  5863.5   66.87
#Mann= 3 , 1 , 0
  4201.6      .1       0  4982.9     .04       0  5043.5      .1       0
#XS Ineff= 2 , 0
       0                    5060       0    65.9
Permanent Ineff=
       F       F
Bank Sta=4982.9,5043.5
XS Rating Curve= 0
Exp/Cntr=.3,.1

Type RM Length L Ch R = 1 ,9666.7  ,755.4,673.6,670.2
BEGIN DESCRIPTION:
Cross Section 9666.7-Interpolated
END DESCRIPTION:
XS GIS Cut Line= 3
      3137333.48      13888731.8      3135940.13     13888754.46
      3134719.93     13888974.97
#Sta/Elev= 30
  3601.7   64.04  3680.9   63.83  4161.7   62.59  4441.7   63.84  4471.7    62.8
  4800.9   62.29  4903.3   62.39  4982.9   61.98  4993.8    55.5  4999.1   54.06
  5011.4   54.05  5045.2   55.45  5055.2   59.14  5075.2   61.87  5105.2      63
  5225.2   61.33  5245.2    62.5  5335.2   61.86  5395.2   63.07  5525.2   61.97
  5555.2   63.47  5695.2   63.09  5805.2   61.02  5865.2   62.71  5985.2   61.06
  6005.2   62.34  6085.2   62.86  6165.2   60.99  6215.2   61.84  6235.2   65.18
#Mann= 6 , 1 , 0
  3601.7      .2       0  3680.9      .1       0  4800.9     .04       0
  4903.3      .1       0  4982.9     .04       0  5075.2      .1       0
#XS Ineff= 2 , 0
       0    4867    63.2    5102       0    63.2
Permanent Ineff=
       F       F
Bank Sta=4982.9,5075.2
XS Rating Curve= 0
Exp/Cntr=.3,.1

Type RM Length L Ch R = 1 ,8993.1  ,330,338,322.1
BEGIN DESCRIPTION:
Cross Section 8993.1-Interpolated
END DESCRIPTION:
XS GIS Cut Line= 6
      3137152.63      13887981.3      3135850.47     13888088.84
      3135788.08     13888111.53      3135788.06     13888111.53
      3135736.81     13888135.92      3134544.18     13888339.86
#Sta/Elev= 30
    3627    63.9    3677    63.7    3707    62.5    3927    62.8    4297    62.2
    4337    62.7    4527    61.4    4547    61.9    4637    62.1  4879.6   61.61
  4897.5   61.57  4963.5      61  4973.5    60.2  4983.5    58.3  4993.5    54.6
  4999.1   53.24  5011.4   53.23    5040    60.2  5236.7    61.3  5266.7    60.3
  5426.7    61.4  5476.7    59.9  5566.7    60.7  5626.7    60.3  5656.7    61.2
  5686.7    60.6  5726.7    60.8  5736.7    60.2  5876.7    61.4  6266.7    62.2
#Mann= 5 , 1 , 0
    3627      .1       0  4879.6     .04       0  4897.5      .1       0
  4973.5     .04       0    5040      .1       0
#XS Ineff= 2 , 0
       0                    5233       0   61.29
Permanent Ineff=
       F       F
Bank Sta=4973.5,5040
XS Rating Curve= 0
Exp/Cntr=.3,.1

Type RM Length L Ch R = 1 ,8655.1  ,77.8,123,215
BEGIN DESCRIPTION:
Cross Section 8655.1-Interpolated
END DESCRIPTION:
XS GIS Cut Line= 4
      3137477.06     13887863.34      3135746.53     13887780.69
      3135573.47     13887820.63      3134431.65     13888025.13
#Sta/Elev= 30
  3168.6    63.9    3356   62.54  3418.6    62.9  3448.6    62.3  3548.6    62.2
  3568.6    62.8  4428.6    61.5  4458.6    62.3  4558.6    61.2  4608.6    61.6
  4618.6    61.1  4668.6    61.7  4941.1    60.5  4961.1      61 4984.44   59.91
 4994.36   53.43 4999.18   51.99 5010.37   51.98 5014.74   52.95 5021.39   59.47
  5078.7    60.4  5668.7    59.9  5718.7    63.5  5748.7    61.9  5788.7    62.2
  5898.7    59.2  5918.7    60.3  5948.7    59.3  5978.7    61.1  6238.7    62.1
#Mann= 4 , 1 , 0
  3168.6      .2       0    3356      .1       0 4984.44     .04       0
 5021.39      .1       0
#XS Ineff= 2 , 0
       0                  5716.4       0    63.6
Permanent Ineff=
       F       F
Bank Sta=4984.44,5021.39
XS Rating Curve= 0
Exp/Cntr=.5,.3

Type RM Length L Ch R = 1 ,8532.1  ,50.2,50.2,50.2
BEGIN DESCRIPTION:
Upstream Section of Bridge/Culvert/Weir
END DESCRIPTION:
XS GIS Cut Line= 5
      3137582.57     13887787.65       3137504.9     13887785.04
       3136249.1     13887721.05      3135402.28     13887679.09
      3134028.35     13887622.31
#Sta/Elev= 30
  3013.7   63.44  3311.2   62.85  3519.3   62.44  3679.3   62.44  4339.3   61.24
 4784.24   61.16 4955.23   60.35 4984.44   59.46 4994.36   52.98 4999.18   51.54
 5006.46    51.7 5010.37   51.53 5014.74    52.5 5021.39   59.02 5037.04   59.64
 5068.98   60.41 5098.01   59.85 5121.67   59.73 5130.13   59.96  5154.7   59.58
 5185.55   60.07  5230.6   59.64  5740.6   59.84  5770.6   59.24  5870.6   59.34
  5990.6   59.84  6190.6   59.54  6407.6   59.54  6487.6   60.54  6571.8   62.94
#Mann= 5 , 1 , 0
  3013.7      .2       0  3311.2      .1       0 4984.44     .04       0
 5021.39      .1       0  6571.8      .2       0
#XS Ineff= 2 , 0
       0  4974.4    61.8  5031.4       0    60.1
Permanent Ineff=
       F       F
Bank Sta=4984.44,5021.39
XS Rating Curve= 0
Exp/Cntr=.5,.3

Type RM Length L Ch R = 2 ,8507.0  ,,,
BEGIN DESCRIPTION:
HARTWICK LANE, SKEW ANGLE OF 25 DEGREES
Structure ID: P84-13
END DESCRIPTION:
Bridge Culvert--1,0,-1,-1, 0
Deck Dist Width WeirC Skew NumUp NumDn MinLoCord MaxHiCord MaxSubmerge Is_Ogee
10,30.2,3,0, 34, 34, , , .95, 0, 1,1,,
  3013.7  3519.3  3679.3  4339.3 4784.24 4876.33 4955.23 4966.88 4984.44 4994.36
 4999.18 5006.46 5010.37 5014.74 5021.39 5037.04 5068.98 5098.01 5121.67 5130.13
  5154.7 5172.54 5185.55  5200.6  5230.6  5416.7  5740.6  5770.6  5870.6  5990.6
  6226.7  6407.6  6487.6  6571.8
    63.4   62.41   62.41   62.08   61.86   61.87      62      62   61.99   61.98
   61.98   61.98   61.97   61.97   61.94   61.79   61.53   61.38   61.26   61.22
   61.21    61.2   61.19   61.18   61.12    60.6   60.48   60.47   60.43   60.39
    60.3   60.67   60.83    62.9
    63.4    62.4    62.4    61.2   61.12   60.57   60.31   60.09   59.42   52.94
    51.5   51.66   51.49   52.46   58.98    59.6   60.37   59.81   59.69   59.92
   59.54    59.9   60.03    59.8    59.6    59.8    59.8    59.2    59.3    59.8
    59.5    59.5    60.5    62.9
  3013.7  3519.3  3679.3  4339.3 4784.24 4876.33 4955.23 4966.88 4984.44 4994.36
 4999.18 5006.46 5010.37 5014.74 5021.39 5037.04 5068.98 5098.01 5121.67 5130.13
  5154.7 5172.54 5185.55  5200.6  5230.6  5416.7  5740.6  5770.6  5870.6  5990.6
  6226.7  6407.6  6487.6  6571.8
    63.4   62.41   62.41   62.08   61.86   61.87      62      62   61.99   61.98
   61.98   61.98   61.97   61.97   61.94   61.79   61.53   61.38   61.26   61.22
   61.21    61.2   61.19   61.18   61.12    60.6   60.48   60.47   60.43   60.39
    60.3   60.67   60.83    62.9
   63.34   62.34   62.34   61.14   61.06   60.51   60.25   60.03   59.36   52.88
   51.44    51.6   51.43    52.4   58.92   59.54   60.31   59.75   59.63   59.86
   59.48   59.84   59.97   59.74   59.54   59.74   59.74   59.14   59.24   59.74
   59.44   59.44   60.44   62.84
BR Coef= 1 , 0 , 0 ,1.25, 0 ,,,.8,-1,2,0,
WSPro=,,,, 1 ,,,, 0 ,,,, 0 ,,,,-1 ,-1 ,-1 , 0 , 0 , 0 , 0 , 0
Culvert=2,8,10,30.2,.015,.4,1,8,1,51.41,5006.8,51.4,5006.8,Culvert #1  , 0 ,10
Culvert Bottom n=.015
BR U #Sta/Elev= 61
  3013.7    63.4  3311.2   62.81  3373.7   62.69  3403.7   62.63  3519.3    62.4
  3679.3    62.4  3913.7   61.96  4269.3    61.3  4339.3    61.2  4760.7   61.12
 4784.24   61.12 4788.88   61.07  4811.4   60.97 4823.55   60.91    4869   60.62
 4876.33   60.57 4955.23   60.31  4959.8   60.22 4966.88   60.09 4984.44   59.42
 4986.09   58.34  4986.2   58.27 4986.31    58.2 4994.36   52.94 4999.18    51.5
 5006.46   51.66 5010.37   51.49 5014.74   52.46    5018   55.66 5021.39   58.98
 5027.99   59.24  5028.1   59.25 5028.31   59.25 5037.04    59.6 5058.42   60.11
  5061.1   60.18 5068.98   60.37 5098.01   59.81 5121.67   59.69  5128.9   59.89
 5130.13   59.92  5154.7   59.54 5172.54    59.9 5185.46   60.02 5185.55   60.03
  5200.6    59.8  5208.9   59.74  5230.6    59.6  5390.6    59.8  5416.7    59.8
  5740.6    59.8  5770.6    59.2  5870.6    59.3  5990.6    59.8  6190.6    59.5
  6226.7    59.5  6247.6    59.5  6407.6    59.5  6487.6    60.5  6571.7    62.9
  6571.8    62.9
BR U #Mann= 5
  3013.7      .2  3311.2      .1 4984.44     .04 5021.39      .1  6571.8      .2
BR U Banks=4984.44,5021.39
BR D #Sta/Elev= 61
  3013.7   63.34  3311.2   62.75  3373.7   62.63  3403.7   62.57  3519.3   62.34
  3679.3   62.34  3913.7    61.9  4269.3   61.24  4339.3   61.14  4760.7   61.06
 4784.24   61.06 4788.88   61.01  4811.4   60.91 4823.55   60.85    4869   60.56
 4876.33   60.51 4955.23   60.25  4959.8   60.16 4966.88   60.03 4984.44   59.36
 4986.09   58.28  4986.2   58.21 4986.31   58.14 4994.36   52.88 4999.18   51.44
 5006.46    51.6 5010.37   51.43 5014.74    52.4    5018    55.6 5021.39   58.92
 5027.99   59.18  5028.1   59.19 5028.31   59.19 5037.04   59.54 5058.42   60.05
  5061.1   60.12 5068.98   60.31 5098.01   59.75 5121.67   59.63  5128.9   59.83
 5130.13   59.86  5154.7   59.48 5172.54   59.84 5185.46   59.96 5185.55   59.97
  5200.6   59.74  5208.9   59.68  5230.6   59.54  5390.6   59.74  5416.7   59.74
  5740.6   59.74  5770.6   59.14  5870.6   59.24  5990.6   59.74  6190.6   59.44
  6226.7   59.44  6247.6   59.44  6407.6   59.44  6487.6   60.44  6571.7   62.84
  6571.8   62.84
BR D #Mann= 5
  3013.7      .2  3311.2      .1 4984.44     .04 5021.39      .1  6571.8      .2
BR D Banks=4984.44,5021.39
BC Design=,, 0 ,, 0 ,,,,,,

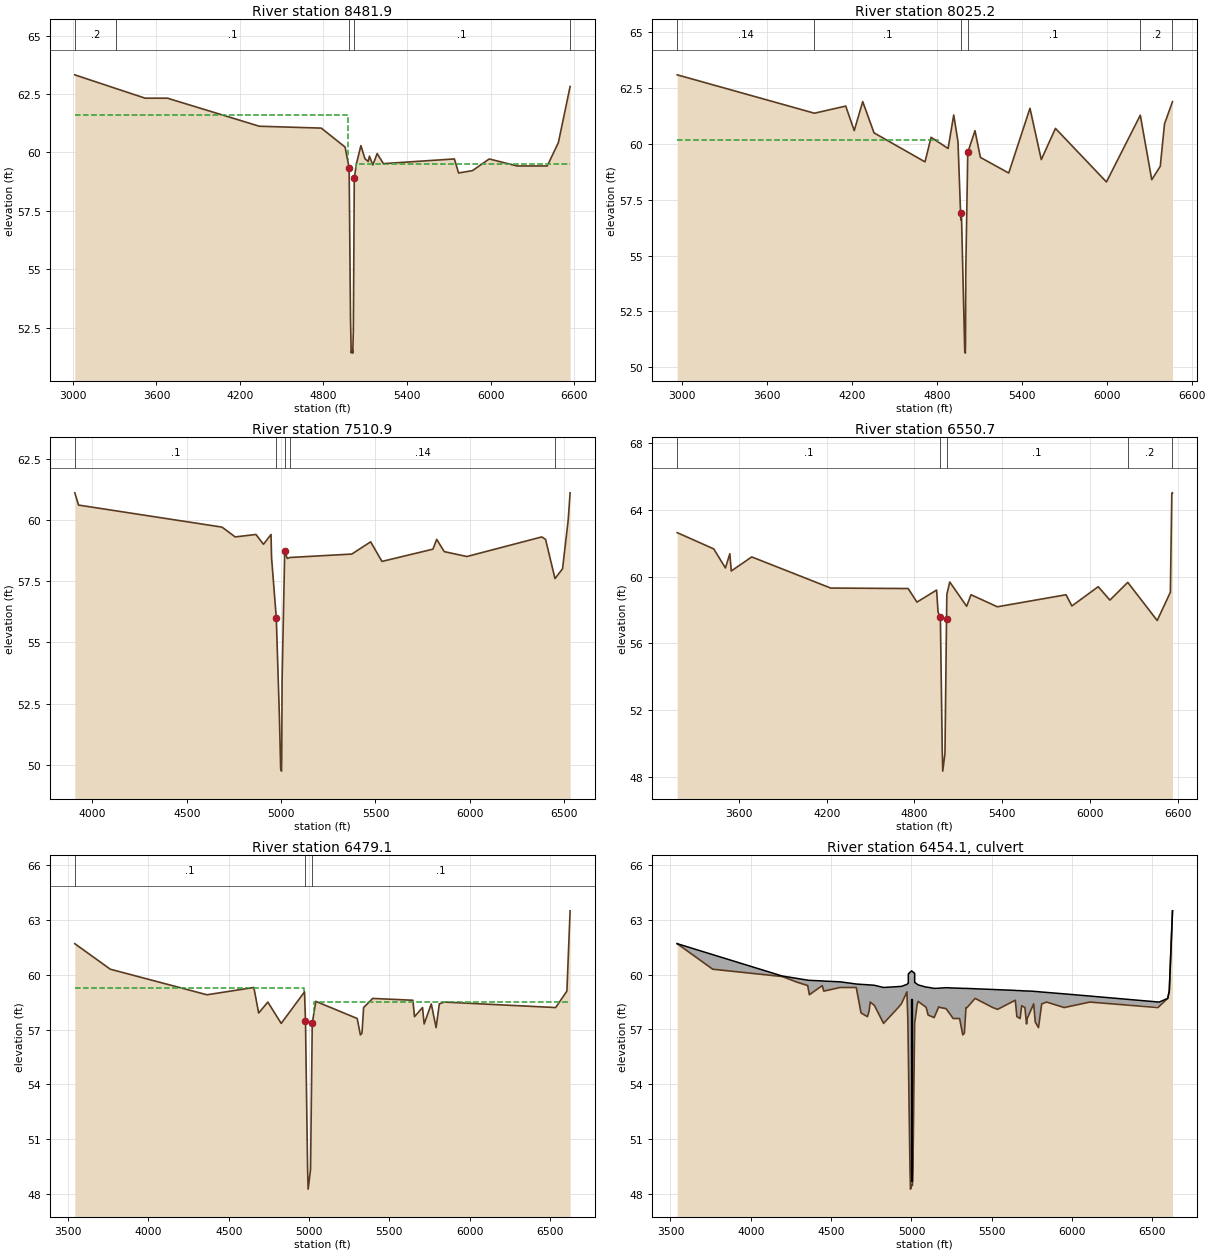
Type RM Length L Ch R = 1 ,8481.9  ,456.7,456.7,456.7
BEGIN DESCRIPTION:
Downstream Section of Bridge/Culvert/Weir
END DESCRIPTION:
XS GIS Cut Line= 5
      3137563.32     13887741.29      3137485.66     13887738.68
      3136229.86     13887674.69      3135383.04     13887632.73
      3134009.11     13887575.95
#Sta/Elev= 30
  3013.7   63.32  3311.2   62.73  3519.3   62.32  3679.3   62.32  4339.3   61.12
 4784.24   61.04 4955.23   60.23 4984.44   59.34 4994.36   52.86 4999.18   51.42
 5006.46   51.58 5010.37   51.41 5014.74   52.38 5021.39    58.9 5037.04   59.52
 5068.98   60.29 5098.01   59.73 5121.67   59.61 5130.13   59.84  5154.7   59.46
 5185.55   59.95  5230.6   59.52  5740.6   59.72  5770.6   59.12  5870.6   59.22
  5990.6   59.72  6190.6   59.42  6407.6   59.42  6487.6   60.42  6571.8   62.82
#Mann= 5 , 1 , 0
  3013.7      .2       0  3311.2      .1       0 4984.44     .04       0
 5021.39      .1       0  6571.8      .2       0
#XS Ineff= 2 , 0
       0  4974.4    61.6  5031.4       0    59.5
Permanent Ineff=
       F       F
Bank Sta=4984.44,5021.39
XS Rating Curve= 0
Exp/Cntr=.5,.3

Type RM Length L Ch R = 1 ,8025.2  ,504.2,514.3,575.6
BEGIN DESCRIPTION:
Cross Section 8025.2-Interpolated
END DESCRIPTION:
XS GIS Cut Line= 5
      3137397.47     13886882.58      3136026.11     13887108.38
      3135626.72     13887161.63      3135320.52     13887248.17
      3133962.59     13887527.74
#Sta/Elev= 30
  2967.4    63.1  3936.5   61.38  4157.4    61.7  4217.4    60.6  4277.4    61.9
  4357.2    60.5  4717.2    59.2  4760.1    60.3  4880.1    59.8  4920.1    61.3
  4950.1    60.1  4970.1    56.6  4974.4   56.89  4997.6   50.74    5002   50.63
  5003.3   51.21  5005.2   54.35  5019.1   59.62  5070.1    60.6  5108.3    59.4
  5308.3    58.7  5458.3    61.6  5538.3    59.3  5638.3    60.7  5998.3    58.3
  6237.4   61.29  6318.3    58.4  6378.3      59  6408.3    60.9  6464.7    61.9
#Mann= 6 , 1 , 0
  2967.4     .14       0  3936.5      .1       0  4974.4     .04       0
  5019.1      .1       0  6237.4      .2       0  6464.7      .2       0
#XS Ineff= 2 , 0
       0    4806    60.2               0
Permanent Ineff=
       F       F
Bank Sta=4974.4,5019.1
XS Rating Curve= 0
Exp/Cntr=.3,.1

Type RM Length L Ch R = 1 ,7510.9  ,915.7,960.2,1016.1
BEGIN DESCRIPTION:
Cross Section 7510.9
END DESCRIPTION:
XS GIS Cut Line= 5
      3136263.59     13886580.07      3135341.34     13886697.78
      3135082.07     13886797.57      3133956.13      13886843.6
      3133688.37     13886732.03
#Sta/Elev= 30
  3906.8    61.1  3926.8    60.6  4686.8    59.7  4756.8    59.3  4866.6    59.4
  4906.6      59  4946.6    59.4  4949.3   58.46  4974.4      56    4991   51.95
  4997.6   49.85    5002   49.74  5003.3   50.32  5005.2   53.46  5019.1   58.73
  5032.7   58.42  5046.1   58.46  5374.4    58.6  5474.4    59.1  5534.4    58.3
  5804.4    58.8  5824.4    59.2  5864.4    58.7  5984.4    58.5  6381.3    59.3
  6401.3    59.2  6451.2    57.6  6491.3      58  6521.3      60  6531.3    61.1
#Mann= 5 , 1 , 0
  3906.8      .1       0  4974.4     .04       0  5019.1      .1       0
  5046.1     .14       0  6451.2      .1       0
Bank Sta=4974.4,5019.1
XS Rating Curve= 0
Exp/Cntr=.3,.1

Type RM Length L Ch R = 1 ,6550.7  ,63.2,71.6,99.3
BEGIN DESCRIPTION:
Cross Section 6550.7-Interpolated
END DESCRIPTION:
XS GIS Cut Line= 5
      3136639.91     13885938.27      3134966.67     13885872.39
      3134741.36     13885878.83      3133498.95     13885827.33
      3133254.33     13885827.33
#Sta/Elev= 30
  3177.6   62.62  3427.6   61.65  3507.6   60.51  3537.6   61.36  3547.6   60.33
  3687.6   61.17  4227.6   59.31  4757.6   59.28  4817.6   58.47  4952.1   59.19
  4962.1   57.86  4977.8   57.59  4990.8   49.55  4994.1   48.37  5009.3   49.44
  5019.8   57.45  5022.1   58.93  5042.1   59.67  5157.5   58.22  5187.5   58.91
  5367.5   58.19  5837.5   58.91  5877.5   58.24  6057.5   59.39  6137.5   58.59
  6259.6   59.65    6461   57.37    6551   59.06    6561   64.98  6565.6      65
#Mann= 5 , 1 , 0
  3177.6      .1       0  4977.8     .04       0  5019.8      .1       0
  6259.6      .2       0  6565.6      .2       0
Bank Sta=4977.8,5019.8
XS Rating Curve= 0
Exp/Cntr=.5,.3

Type RM Length L Ch R = 1 ,6479.1  ,50,50,50
BEGIN DESCRIPTION:
Upstream Section of Bridge/Culvert/Weir
END DESCRIPTION:
XS GIS Cut Line= 6
      3136271.38     13885743.37      3135569.35     13885724.57
      3135255.86     13885807.86      3135194.09     13885813.31
      3134087.69     13885764.97      3133201.05     13885732.23
#Sta/Elev= 30
  3541.7   61.71  3762.9   60.31  4364.4   58.91  4656.3   59.31  4686.3   57.91
  4743.4   58.51  4826.6   57.34  4971.7   59.07  4977.8   57.48  4990.8   49.44
  4994.1   48.26  5009.3   49.33  5019.8   57.34  5041.9   58.55  5299.6   57.61
  5319.6   56.71  5329.6   56.81  5339.6   58.21  5396.4   58.71  5646.4   58.61
  5656.4   57.71  5706.4   58.21  5716.4   57.31  5760.9   58.41  5790.9   57.11
  5810.9   58.41  5840.9   58.51  6535.1   58.21  6605.1   59.11  6625.1   63.51
#Mann= 3 , 1 , 0
  3541.7      .1       0  4977.8     .04       0  5019.8      .1       0
#XS Ineff= 2 , 0
       0  4967.8    59.3    5030       0    58.5
Permanent Ineff=
       F       F
Bank Sta=4977.8,5019.8
XS Rating Curve= 0
Exp/Cntr=.5,.3

Type RM Length L Ch R = 2 ,6454.1  ,,,
BEGIN DESCRIPTION:
HOPPER ROAD
Structure ID: P84-12
END DESCRIPTION:
Bridge Culvert--1,0,-1,-1, 0
Deck Dist Width WeirC Skew NumUp NumDn MinLoCord MaxHiCord MaxSubmerge Is_Ogee
10,30,3,0, 60, 60, , , .95, 0, 1,1,,
  3541.7  3762.9  4194.4  4354.4  4364.4  4444.4  4454.4  4556.3  4656.3  4686.3
  4726.3  4736.3  4743.4  4769.1  4826.6  4937.9  4971.7  4977.8 4980.39  4980.5
  4990.8  4994.1  5000.7  5005.8  5009.3  5019.8  5020.1 5020.21  5035.8  5041.9
  5091.8  5103.5  5141.4  5170.1  5215.8  5259.6  5299.6  5319.6  5329.6  5339.6
  5396.4  5536.4  5646.4  5656.4  5676.4  5686.4  5706.4  5716.4  5720.9  5760.9
  5770.9  5790.9  5810.9  5840.9  5950.9  6110.9  6541.8  6595.1  6605.1  6625.1
    61.7    61.1   59.93    59.7   59.69   59.66   59.65   59.61   59.49   59.47
   59.45   59.44   59.44   59.42    59.3   59.36   59.47   59.52   59.54   60.04
   60.13   60.15   60.21   60.18   60.15   60.08   60.08   59.58   59.48   59.44
   59.32   59.31   59.25   59.26   59.29   59.27   59.26   59.25   59.25   59.25
   59.23   59.18   59.14   59.13   59.13   59.12   59.11   59.11   59.11   59.09
   59.08   59.07   59.05   59.03   58.95   58.83    58.5    58.7    59.1    63.5
    61.7    60.3    59.9    59.4    58.9    59.4    59.1    59.3    59.3    57.9
    57.7      58    58.5   58.32   57.33   58.41   59.06   57.47   55.87    55.8
   49.43   48.25   48.46   48.45   49.32   57.33   57.35   57.36   58.39   58.54
   58.21   57.79   57.65   58.24   58.14    57.6    57.6    56.7    56.8    58.2
    58.7    58.1    58.6    57.7    57.6    58.3    58.2    57.3    57.6    58.4
    57.4    57.1    58.4    58.5    58.2    58.5   58.26    58.7    59.1    63.5
  3541.7  3762.9  4194.4  4354.4  4364.4  4444.4  4454.4  4556.3  4656.3  4686.3
  4726.3  4736.3  4743.4  4769.1  4826.6  4937.9  4971.7  4977.8 4980.39  4980.5
  4990.8  4994.1  5000.7  5005.8  5009.3  5019.8  5020.1 5020.21  5035.8  5041.9
  5091.8  5103.5  5141.4  5170.1  5215.8  5259.6  5299.6  5319.6  5329.6  5339.6
  5396.4  5536.4  5646.4  5656.4  5676.4  5686.4  5706.4  5716.4  5720.9  5760.9
  5770.9  5790.9  5810.9  5840.9  5950.9  6110.9  6541.8  6595.1  6605.1  6625.1
    61.7    61.1   59.93    59.7   59.69   59.66   59.65   59.61   59.49   59.47
   59.45   59.44   59.44   59.42    59.3   59.36   59.47   59.52   59.54   60.04
   60.13   60.15   60.21   60.18   60.15   60.08   60.08   59.58   59.48   59.44
   59.32   59.31   59.25   59.26   59.29   59.27   59.26   59.25   59.25   59.25
   59.23   59.18   59.14   59.13   59.13   59.12   59.11   59.11   59.11   59.09
   59.08   59.07   59.05   59.03   58.95   58.83    58.5    58.7    59.1    63.5
   61.58   60.18   59.78   59.28   58.78   59.28   58.98   59.18   59.18   57.78
   57.58   57.88   58.38    58.2   57.21   58.29   58.94   57.35   55.75   55.68
   49.31   48.13   48.34   48.33    49.2   57.21   57.23   57.24   58.27   58.42
   58.09   57.67   57.53   58.12   58.02   57.48   57.48   56.58   56.68   58.08
   58.58   57.98   58.48   57.58   57.48   58.18   58.08   57.18   57.48   58.28
   57.28   56.98   58.28   58.38   58.08   58.38   58.14   58.58   58.98   63.38
BR Coef= 1 , 0 , 0 ,1.25, 0 ,,,.8,-1,2,0,
WSPro=,,,, 1 ,,,, 0 ,,,, 0 ,,,,-1 ,-1 ,-1 , 0 , 0 , 0 , 0 , 0
Culvert=2,10,10,30,.015,.4,1,8,1,48.69,5000.9,48.65,5000.9,Culvert #1  , 0 ,10
Culvert Bottom n=.015
BR U #Sta/Elev= 80
  3541.7    61.7  3762.9    60.3  4194.4    59.9  4243.9   59.74  4284.4    59.6
  4352.5   59.41  4354.4    59.4  4364.4    58.9  4444.4    59.4  4454.4    59.1
  4556.3    59.3  4568.4    59.3  4630.4    59.3  4656.3    59.3  4686.3    57.9
  4726.3    57.7  4736.3      58  4743.4    58.5  4763.3   58.36  4769.1   58.32
  4826.6   57.33  4831.6   57.38  4920.2   58.22  4937.9   58.41  4960.4   58.84
  4971.7   59.06  4977.8   57.47 4980.39   55.87  4980.5    55.8 4980.61   55.73
  4990.8   49.43  4994.1   48.25  5000.7   48.46  5000.8   48.46  5005.8   48.45
  5009.3   49.32  5019.8   57.33 5019.99   57.34  5020.1   57.35 5020.21   57.36
  5035.8   58.39  5041.9   58.54  5051.8   58.47  5091.8   58.21  5103.5   57.79
  5141.4   57.65  5142.4   57.67  5170.1   58.24  5180.2    58.2  5215.8   58.14
  5216.3   58.13  5259.6    57.6  5299.6    57.6  5319.6    56.7  5329.6    56.8
  5339.6    58.2  5346.4    58.2  5396.4    58.7  5506.4    58.2  5536.4    58.1
  5646.4    58.6  5656.4    57.7  5676.4    57.6  5686.4    58.3  5706.4    58.2
  5716.4    57.3  5720.9    57.6  5747.8   58.14  5760.9    58.4  5770.9    57.4
  5790.9    57.1  5810.9    58.4  5840.9    58.5  5950.9    58.2  6110.9    58.5
  6535.1    58.2  6541.8   58.26  6595.1    58.7  6605.1    59.1  6625.1    63.5
BR U #Mann= 3
  3541.7      .1  4977.8     .04  5019.8      .1
BR U Banks=4977.8,5019.8
BR D #Sta/Elev= 80
  3541.7   61.58  3762.9   60.18  4194.4   59.78  4243.9   59.62  4284.4   59.48
  4352.5   59.29  4354.4   59.28  4364.4   58.78  4444.4   59.28  4454.4   58.98
  4556.3   59.18  4568.4   59.18  4630.4   59.18  4656.3   59.18  4686.3   57.78
  4726.3   57.58  4736.3   57.88  4743.4   58.38  4763.3   58.24  4769.1    58.2
  4826.6   57.21  4831.6   57.26  4920.2    58.1  4937.9   58.29  4960.4   58.72
  4971.7   58.94  4977.8   57.35 4980.39   55.75  4980.5   55.68 4980.61   55.61
  4990.8   49.31  4994.1   48.13  5000.7   48.34  5000.8   48.34  5005.8   48.33
  5009.3    49.2  5019.8   57.21 5019.99   57.22  5020.1   57.23 5020.21   57.24
  5035.8   58.27  5041.9   58.42  5051.8   58.35  5091.8   58.09  5103.5   57.67
  5141.4   57.53  5142.4   57.55  5170.1   58.12  5180.2   58.08  5215.8   58.02
  5216.3   58.01  5259.6   57.48  5299.6   57.48  5319.6   56.58  5329.6   56.68
  5339.6   58.08  5346.4   58.08  5396.4   58.58  5506.4   58.08  5536.4   57.98
  5646.4   58.48  5656.4   57.58  5676.4   57.48  5686.4   58.18  5706.4   58.08
  5716.4   57.18  5720.9   57.48  5747.8   58.02  5760.9   58.28  5770.9   57.28
  5790.9   56.98  5810.9   58.28  5840.9   58.38  5950.9   58.08  6110.9   58.38
  6535.1   58.08  6541.8   58.14  6595.1   58.58  6605.1   58.98  6625.1   63.38
BR D #Mann= 3
  3541.7      .1  4977.8     .04  5019.8      .1
BR D Banks=4977.8,5019.8
BC Design=,, 0 ,, 0 ,,,,,,

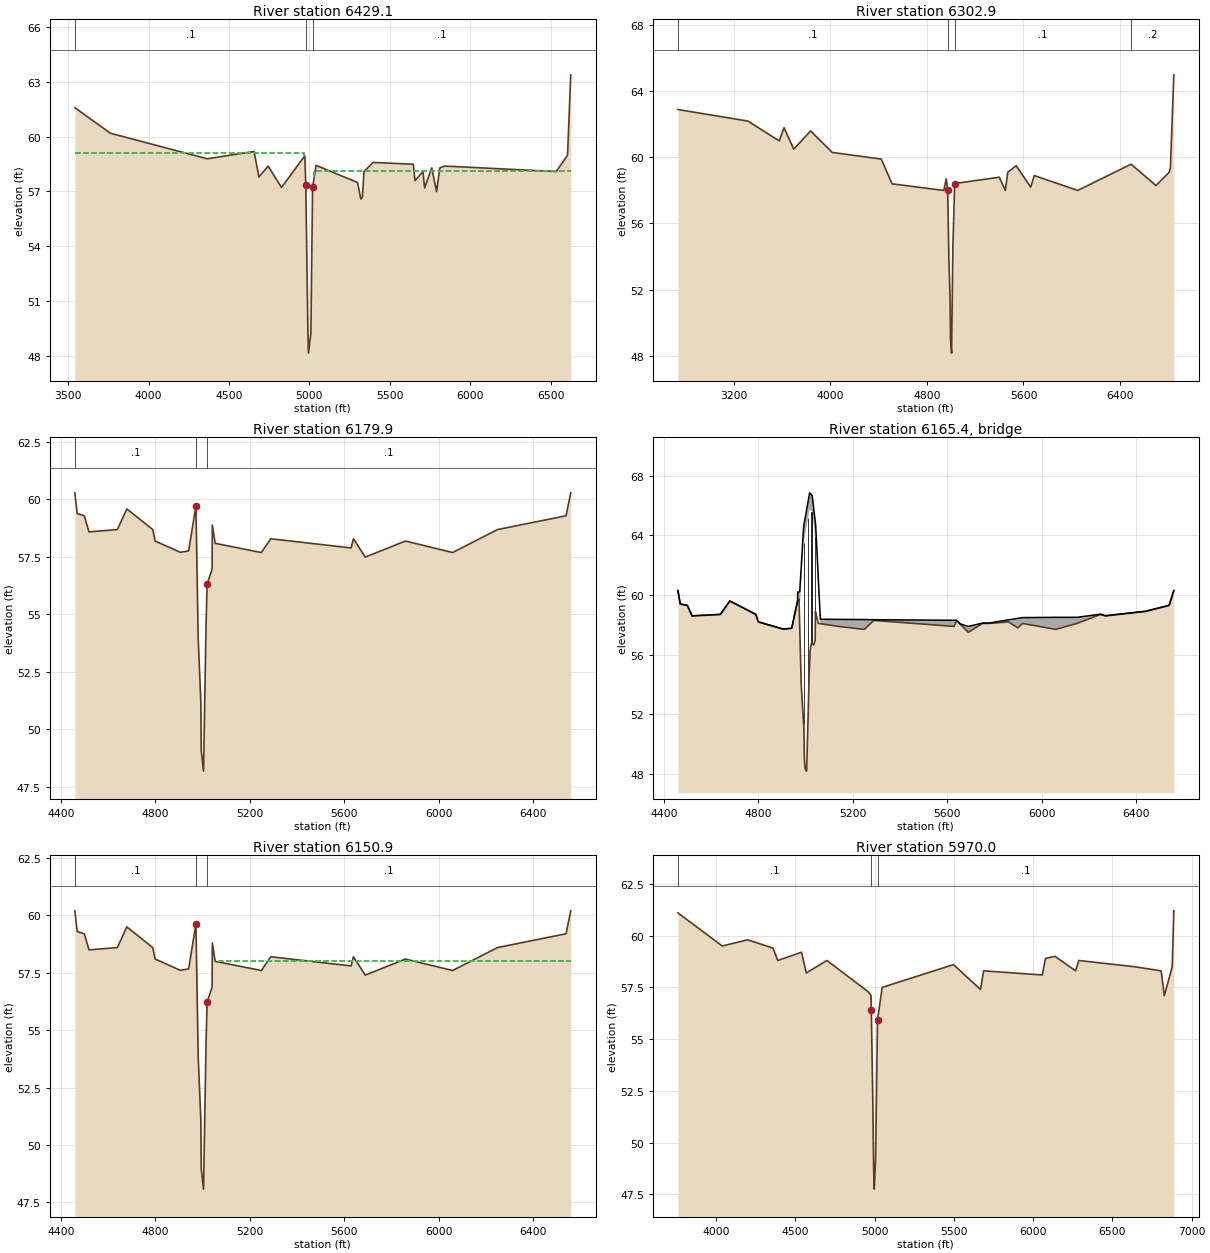
Type RM Length L Ch R = 1 ,6429.1  ,126.2,126.2,126.2
BEGIN DESCRIPTION:
Downstream Section of Bridge/Culvert/Weir
END DESCRIPTION:
XS GIS Cut Line= 6
      3136272.16     13885693.38      3135570.13     13885674.57
      3135256.64     13885757.86      3135194.87     13885763.31
      3134088.47     13885714.97      3133201.83     13885682.24
#Sta/Elev= 30
  3541.7   61.58  3762.9   60.18  4364.4   58.78  4656.3   59.18  4686.3   57.78
  4743.4   58.38  4826.6   57.21  4971.7   58.94  4977.8   57.35  4990.8   49.31
  4994.1   48.13  5009.3    49.2  5019.8   57.21  5041.9   58.42  5299.6   57.48
  5319.6   56.58  5329.6   56.68  5339.6   58.08  5396.4   58.58  5646.4   58.48
  5656.4   57.58  5706.4   58.08  5716.4   57.18  5760.9   58.28  5790.9   56.98
  5810.9   58.28  5840.9   58.38  6535.1   58.08  6605.1   58.98  6625.1   63.38
#Mann= 3 , 1 , 0
  3541.7      .1       0  4977.8     .04       0  5019.8      .1       0
#XS Ineff= 2 , 0
       0  4967.8    59.1    5030       0    58.1
Permanent Ineff=
       F       F
Bank Sta=4977.8,5019.8
XS Rating Curve= 0
Exp/Cntr=.5,.3

Type RM Length L Ch R = 1 ,6302.9  ,119.7,123,142.7
BEGIN DESCRIPTION:
Cross Section 6302.9-Interpolated
END DESCRIPTION:
XS GIS Cut Line= 5
      3137089.79     13885658.39      3135675.57     13885599.75
      3135007.64     13885635.28      3133160.19     13885571.33
      3132995.92     13885502.44
#Sta/Elev= 30
  2735.4    62.9  3315.4    62.2  3575.4      61  3615.4    61.8  3695.4    60.5
  3835.4    61.6  4015.4    60.3  4420.9    59.9  4510.9    58.4  4939.7      58
  4959.7    58.7    4972   58.02  4981.5   53.94  4992.7   51.17  4994.6   49.03
  5004.2   48.15  5014.8   54.55  5029.6   58.42  5399.7    58.8  5449.7      58
  5469.7    59.1  5539.7    59.5  5659.7    58.2  5689.7    58.9  6049.7      58
    6492   59.59  6698.3    58.3  6808.3    59.1  6818.3    59.4  6846.4      65
#Mann= 4 , 1 , 0
  2735.4      .1       0    4972     .04       0  5029.6      .1       0
    6492      .2       0
Bank Sta=4972,5029.6
XS Rating Curve= 0
Exp/Cntr=.5,.3

Type RM Length L Ch R = 1 ,6179.9  ,29,29,29
BEGIN DESCRIPTION:
Upstream Section of Bridge/Culvert/Weir
END DESCRIPTION:
XS GIS Cut Line= 3
      3135385.04     13885465.59      3135051.57     13885458.97
      3133286.85     13885392.55
#Sta/Elev= 30
  4459.3   60.29  4469.3   59.39  4499.3   59.29  4519.3   58.59  4639.3   58.69
  4679.3   59.59  4789.3   58.69  4799.3   58.19  4905.9    57.7  4941.1   57.76
    4972   59.72  4981.5   53.96  4992.7   51.19  4994.5   49.05  5004.2   48.17
  5014.8   54.57  5019.4   56.32  5040.4   56.96  5041.4   58.89  5053.4   58.09
  5248.8   57.69  5288.8   58.29  5628.8   57.89  5638.8   58.29  5688.8   57.49
  5858.8   58.19  6058.8   57.69  6248.8   58.69  6538.8   59.29  6558.8   60.29
#Mann= 3 , 1 , 0
  4459.3      .1       0    4972     .04       0  5019.4      .1       0
#XS Ineff= 2 , 0
       0  4964.9    57.7  5071.5       0   58.05
Permanent Ineff=
       F       F
Bank Sta=4972,5019.4
XS Rating Curve= 0
Exp/Cntr=.5,.3

Type RM Length L Ch R = 3 ,6165.4  ,,,
BEGIN DESCRIPTION:
HANLEY LANE
Structure ID: P84-11
END DESCRIPTION:
Bridge Culvert--1,0,-1,-1, 0
Deck Dist Width WeirC Skew NumUp NumDn MinLoCord MaxHiCord MaxSubmerge Is_Ogee
10,9,2.6,0, 41, 41, , , .95, 0, 1,1,,
  4459.3  4469.3  4499.3  4519.3  4639.3  4679.3  4789.3  4799.3  4905.9  4941.1
  4965.7 4966.69    4972 4975.01  4975.1  4991.7  5017.1  5027.7  5042.6  5053.4
 5061.59 5061.81  5062.5  5248.8  5288.8  5628.8  5638.8  5654.6  5688.8  5748.8
  5778.8  5858.8  5898.8  5918.8  6058.8  6148.8  6248.8  6268.8  6438.8  6538.8
  6558.8
    60.3    59.4    59.3    58.6    58.7    59.6    58.7    58.2   57.71   57.77
   59.59    60.2    60.2   60.23   60.25   64.61   66.86   66.67   64.69   61.25
   58.64   58.64   58.37   58.35   58.34    58.3   58.31   58.06   57.89   58.11
   58.12   58.33   58.43   58.48    58.5    58.5   58.71   58.61   58.91   59.31
    60.3
   60.29   59.39   59.29   58.59   58.69   59.59   58.69   58.19    57.7   57.76
   59.58    59.6   59.72   57.84   59.14    63.5   65.75   65.56   63.58   60.14
   58.07   58.07   58.07   57.69   58.29   57.89   58.29   58.04   57.49   58.09
   58.09   58.19   57.79   58.09   57.69   58.09   58.69   58.59   58.89   59.29
   60.29
  4459.3  4469.3  4499.3  4519.3  4639.3  4679.3  4789.3  4799.3  4905.9  4941.1
  4965.7 4966.69    4972 4975.01  4975.1  4991.7  5017.1  5027.7  5042.6  5053.4
 5061.59 5061.81  5062.5  5248.8  5288.8  5628.8  5638.8  5654.6  5688.8  5748.8
  5778.8  5858.8  5898.8  5918.8  6058.8  6148.8  6248.8  6268.8  6438.8  6538.8
  6558.8
    60.3    59.4    59.3    58.6    58.7    59.6    58.7    58.2   57.71   57.77
   59.59    60.2    60.2   60.23   60.25   64.61   66.86   66.67   64.69   61.25
   58.64   58.64   58.37   58.35   58.34    58.3   58.31   58.06   57.89   58.11
   58.12   58.33   58.43   58.48    58.5    58.5   58.71   58.61   58.91   59.31
    60.3
   60.22   59.32   59.22   58.52   58.62   59.52   58.62   58.12   57.63   57.69
   59.51   59.53   59.65   57.77   59.07   63.43   65.68   65.49   63.51   60.07
      58      58      58   57.62   58.22   57.82   58.22   57.97   57.42   58.02
   58.02   58.12   57.72   58.02   57.62   58.02   58.62   58.52   58.82   59.22
   60.22
Pier Skew, UpSta & Num, DnSta & Num=  ,4991.8, 2 ,4991.8, 2 , 0 , 0 , 0 ,,
       1       1
   50.24   64.55
       1       1
   50.17   64.48
Pier Skew, UpSta & Num, DnSta & Num=  ,5010.4, 2 ,5010.4, 2 , 0 , 0 , 0 ,,
       1       1
   50.46    66.2
       1       1
   50.39   66.13
Pier Skew, UpSta & Num, DnSta & Num=  ,5025.3, 2 ,5025.3, 2 , 0 , 0 , 0 ,,
       1       1
   55.77   66.61
       1       1
    55.7   66.54
Pier Skew, UpSta & Num, DnSta & Num=  ,5040.4, 2 ,5040.4, 2 , 0 , 0 , 0 ,,
       1       1
   55.93   64.94
       1       1
   55.87   64.87
Abutment Skew #Up #Dn= , 2 , 2
  4974.9  4976.3
   59.14   57.04
  4974.9  4976.3
   59.07   56.97
BR Coef= 1 , 1 , 0 ,1.25, 0 ,,,.8,0,2,0,
WSPro=,,,, 1 ,,,, 0 ,,,, 0 ,,,,-1 ,-1 ,-1 , 0 , 0 , 0 , 0 , 0
BR U #Sta/Elev= 71
  4459.3   60.29  4469.3   59.39  4499.3   59.29  4519.3   58.59  4639.3   58.69
  4679.3   59.59  4789.3   58.69  4799.3   58.19  4905.9    57.7    4906   57.71
  4941.1   57.76  4965.7   59.58 4966.69    59.6  4966.8    59.6 4966.91   59.61
    4972   59.72  4974.9   57.91 4975.01   57.84  4975.1   57.79  4976.2    57.1
  4976.3   57.04  4981.5   53.96  4988.4   52.09  4991.7   51.33  4991.8   51.31
  4992.7   51.19  4994.5   49.05  4997.1   48.47  4999.3   48.27  5004.2   48.17
  5005.4   48.91  5010.4   51.74  5014.8   54.57  5017.1   55.45  5019.4   56.32
  5025.3   56.81  5027.7   56.76    5034   56.64  5040.4   56.96  5041.4   58.89
  5042.6   58.81  5053.4   58.09 5061.59   58.07  5061.7   58.07 5061.81   58.07
  5062.3   58.07 5062.39   58.07  5062.5   58.07  5062.6   58.07  5143.5   57.88
  5248.8   57.69  5288.8   58.29  5628.8   57.89  5634.6   58.12  5638.8   58.29
  5654.6   58.04  5688.8   57.49  5748.8   58.09  5778.8   58.09  5858.8   58.19
  5898.8   57.79  5918.8   58.09  5924.6   58.07  6058.8   57.69  6148.8   58.09
  6248.8   58.69  6268.8   58.59  6438.8   58.89  6538.8   59.29  6544.6   59.58
  6558.8   60.29
BR U #Mann= 3
  4459.3      .1    4972     .04  5019.4      .1
BR U Banks=4972,5019.4
BR D #Sta/Elev= 71
  4459.3   60.22  4469.3   59.32  4499.3   59.22  4519.3   58.52  4639.3   58.62
  4679.3   59.52  4789.3   58.62  4799.3   58.12  4905.9   57.63    4906   57.64
  4941.1   57.69  4965.7   59.51 4966.69   59.53  4966.8   59.53 4966.91   59.54
    4972   59.65  4974.9   57.84 4975.01   57.77  4975.1   57.72  4976.2   57.03
  4976.3   56.97  4981.5   53.89  4988.4   52.02  4991.7   51.26  4991.8   51.24
  4992.7   51.12  4994.5   48.98  4997.1    48.4  4999.3    48.2  5004.2    48.1
  5005.4   48.84  5010.4   51.67  5014.8    54.5  5017.1   55.38  5019.4   56.25
  5025.3   56.74  5027.7   56.69    5034   56.57  5040.4   56.89  5041.4   58.82
  5042.6   58.74  5053.4   58.02 5061.59      58  5061.7      58 5061.81      58
  5062.3      58 5062.39      58  5062.5      58  5062.6      58  5143.5   57.81
  5248.8   57.62  5288.8   58.22  5628.8   57.82  5634.6   58.05  5638.8   58.22
  5654.6   57.97  5688.8   57.42  5748.8   58.02  5778.8   58.02  5858.8   58.12
  5898.8   57.72  5918.8   58.02  5924.6      58  6058.8   57.62  6148.8   58.02
  6248.8   58.62  6268.8   58.52  6438.8   58.82  6538.8   59.22  6544.6   59.51
  6558.8   60.22
BR D #Mann= 3
  4459.3      .1    4972     .04  5019.4      .1
BR D Banks=4972,5019.4
BC Design=,, 0 ,, 0 ,,,,,,

Type RM Length L Ch R = 1 ,6150.9  ,180.9,180.9,180.9
BEGIN DESCRIPTION:
Downstream Section of Bridge/Culvert/Weir
END DESCRIPTION:
XS GIS Cut Line= 3
       3135389.2     13885436.89      3135055.73     13885430.27
      3133291.01     13885363.85
#Sta/Elev= 30
  4459.3    60.2  4469.3    59.3  4499.3    59.2  4519.3    58.5  4639.3    58.6
  4679.3    59.5  4789.3    58.6  4799.3    58.1  4905.9   57.61  4941.1   57.67
    4972   59.63  4981.5   53.87  4992.7    51.1  4994.5   48.96  5004.2   48.08
  5014.8   54.48  5019.4   56.23  5040.4   56.87  5041.4    58.8  5053.4      58
  5248.8    57.6  5288.8    58.2  5628.8    57.8  5638.8    58.2  5688.8    57.4
  5858.8    58.1  6058.8    57.6  6248.8    58.6  6538.8    59.2  6558.8    60.2
#Mann= 3 , 1 , 0
  4459.3      .1       0    4972     .04       0  5019.4      .1       0
#XS Ineff= 2 , 0
       0  4964.9    57.7  5071.5       0      58
Permanent Ineff=
       F       F
Bank Sta=4972,5019.4
XS Rating Curve= 0
Exp/Cntr=.5,.3

Type RM Length L Ch R = 1 ,5970.0  ,152.3,146.4,138.9
BEGIN DESCRIPTION:
Cross Section 5970.0-Interpolated
END DESCRIPTION:
XS GIS Cut Line= 4
      3136113.29     13885325.41      3135014.75     13885308.42
      3133238.35     13885201.84      3132995.78     13885262.48
#Sta/Elev= 30
  3759.2    61.1  4039.2    59.5  4199.2    59.8  4359.2    59.4  4389.2    58.8
  4539.2    59.2  4569.2    58.2  4699.2    58.8  4957.9    57.3  4977.9    57.1
  4979.2   56.42  4988.7   52.06    4994   48.67  4997.6   47.75  5006.1    49.2
  5018.5   55.93  5047.9    57.5  5497.9    58.6  5667.9    57.4  5687.9    58.3
  6057.9    58.1  6077.9    58.9  6137.9      59  6267.9    58.3  6287.9    58.8
  6637.5    58.5  6807.5    58.3  6827.5    57.1  6877.5    58.5  6887.5    61.2
#Mann= 3 , 1 , 0
  3759.2      .1       0  4979.2     .04       0  5018.5      .1       0
Bank Sta=4979.2,5018.5
XS Rating Curve= 0
Exp/Cntr=.5,.3