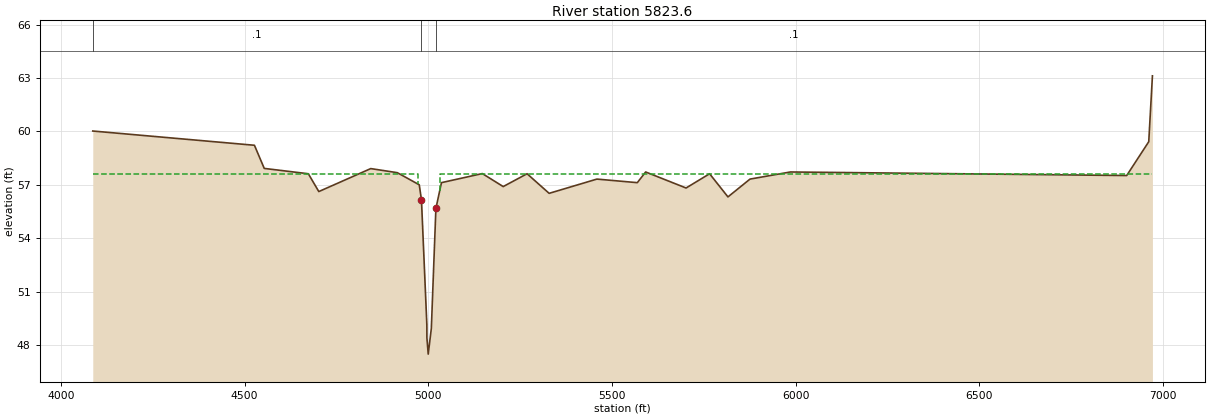
HEC-RAS study P118-14-00.PRJ: P118-14-00

--- P118-14-00.g01 (geometry) --- (continued)

Type RM Length L Ch R = 1 ,5823.6  ,47,47,47
BEGIN DESCRIPTION:
Upstream Section of Bridge/Culvert/Weir
END DESCRIPTION:
XS GIS Cut Line= 4
      3135790.86     13885185.73      3135290.13     13885173.45
      3134174.67     13885124.95      3132909.12      13885070.7
#Sta/Elev= 30
  4086.6   60.02  4526.6   59.22  4553.3   57.92  4673.3   57.62  4701.8   56.62
  4843.2   57.91  4915.5   57.68  4975.2      57  4981.2   56.16  4995.9   49.13
    4996   48.41  4999.6   47.49  5008.1   48.94  5020.5   55.67  5035.6   57.12
  5146.9   57.63  5203.7    56.9  5268.7   57.62  5328.7   56.52  5458.7   57.32
  5568.7   57.12  5591.4   57.72  5701.4   56.82  5765.4   57.62  5815.4   56.32
  5875.4   57.32  5985.4   57.72  6900.7   57.52  6960.7   59.42  6970.7   63.12
#Mann= 3 , 1 , 0
  4086.6      .1       0  4981.2     .04       0  5020.5      .1       0
#XS Ineff= 2 , 0
       0  4971.2    57.6  5030.5       0    57.6
Permanent Ineff=
       F       F
Bank Sta=4981.2,5020.5
XS Rating Curve= 0
Exp/Cntr=.5,.3