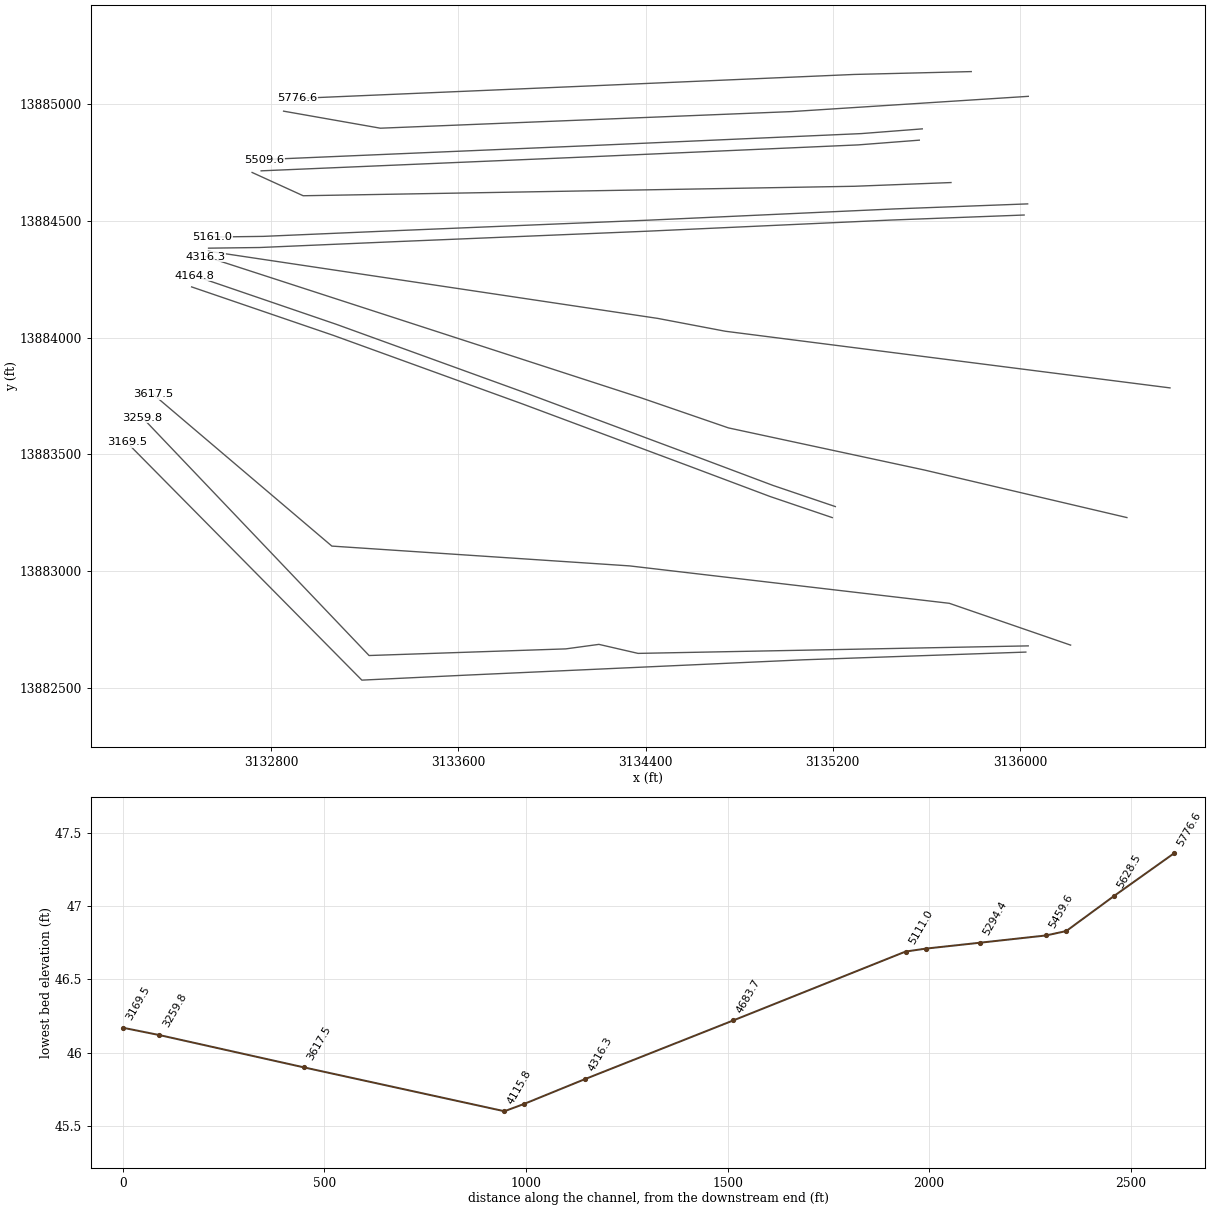
HEC-RAS study P118-14-00.PRJ: P118-14-00

--- P118-14-00.g01 (geometry) --- (continued)

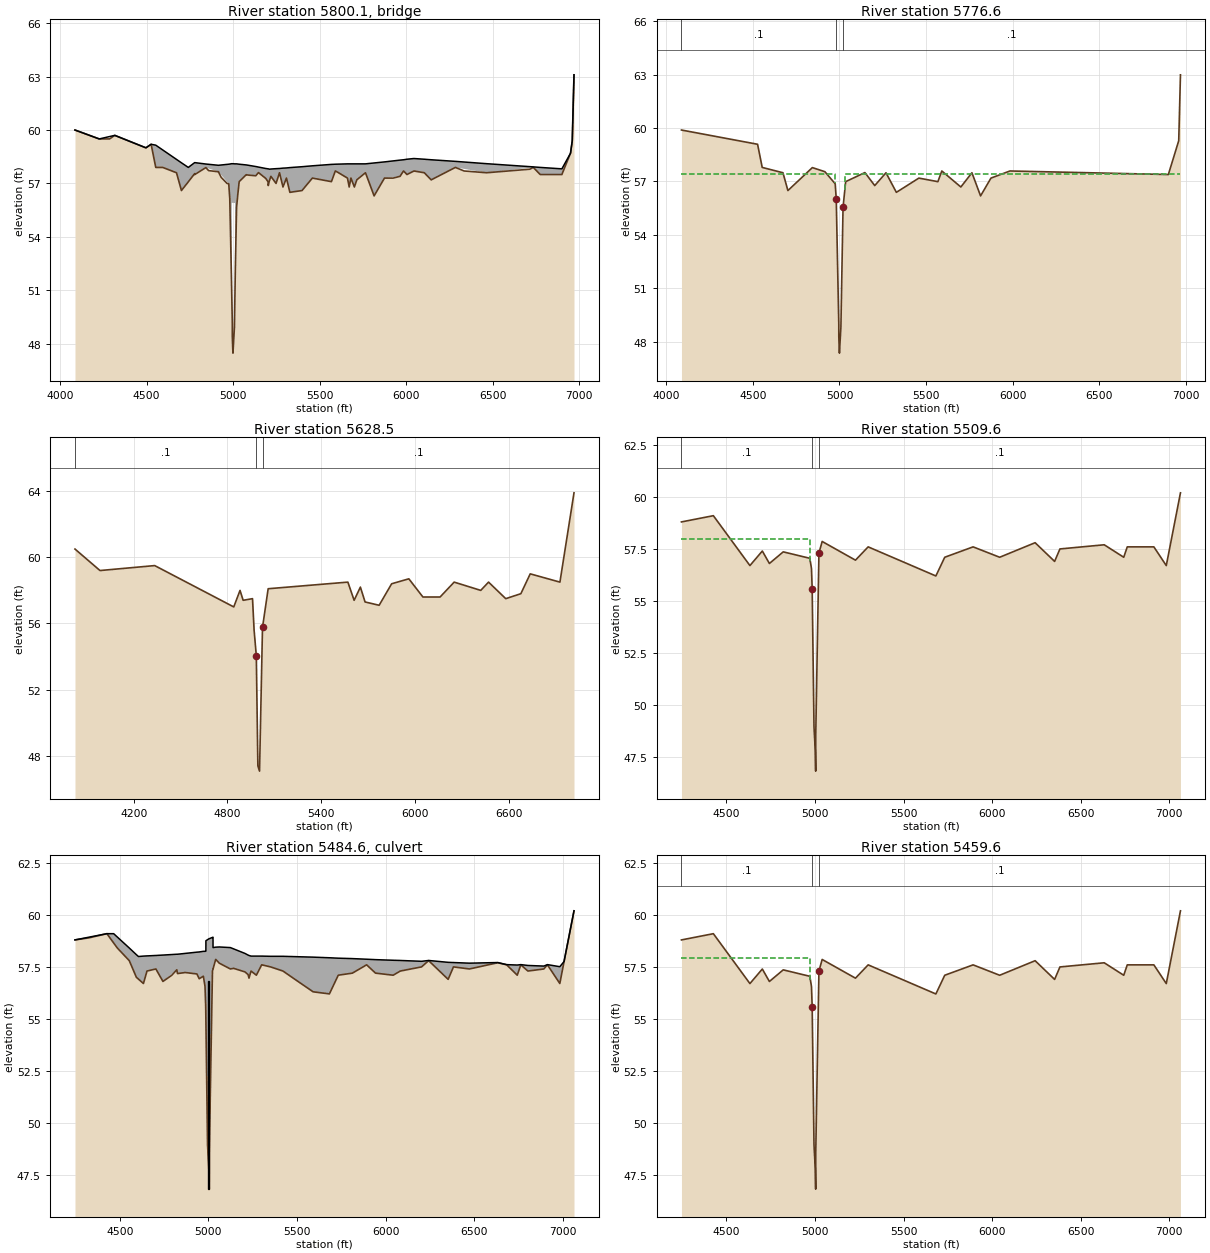
Type RM Length L Ch R = 3 ,5800.1  ,,,
BEGIN DESCRIPTION:
MOHAWK LANE
Structure ID: P84-10
END DESCRIPTION:
Bridge Culvert--1,0,-1,-1, 0
Deck Dist Width WeirC Skew NumUp NumDn MinLoCord MaxHiCord MaxSubmerge Is_Ogee
10,27,2.6,0, 60, 60, , , .95, 0, 1,1,,
  4086.6  4226.6  4316.6  4496.6  4526.6  4553.3  4673.3  4701.8  4741.5  4778.3
  4843.2  4915.5  4975.2  4981.2 4993.01  4993.1 5011.19  5011.3  5013.3  5020.5
  5035.6  5076.4  5131.7  5146.9  5189.2  5202.6  5203.7  5211.5  5218.7  5248.7
  5268.7  5288.7  5308.7  5328.7  5398.7  5458.7  5568.7  5591.4  5661.4  5671.4
  5681.4  5701.4  5715.4  5765.4  5815.4  5875.4  5965.4  5985.4  6005.4  6045.4
  6105.4  6145.4  6285.4  6465.4  6735.4  6775.4  6900.7  6950.7  6960.7  6970.7
      60    59.5    59.7      59    59.2   59.15   58.35   58.16    57.9   58.17
   58.09   58.02   58.08   58.09   58.11   58.11    58.1    58.1    58.1    58.1
   58.08   58.04   57.95   57.92   57.84   57.82   57.82    57.8   57.81   57.83
   57.84   57.86   57.87   57.89   57.94   57.99   58.07   58.08    58.1    58.1
    58.1    58.1    58.1    58.1   58.15   58.21   58.31   58.33   58.36    58.4
   58.36   58.33   58.24   58.11   57.93    57.9   57.82    58.7    59.4    63.1
      60    59.5    59.7      59    59.2    57.9    57.6    56.6   57.09   57.55
   57.89   57.66   56.98   56.14   50.59   55.91    55.9   50.91   52.15   55.65
    57.1   57.49   57.43   57.61   57.28   57.09   56.88   57.18    57.4      57
    57.6    56.8    57.3    56.5    56.6    57.3    57.1    57.7    57.3    56.8
    57.3    56.8    57.2    57.6    56.3    57.3    57.4    57.7    57.5    57.7
    57.6    57.2    57.9    57.6    57.9    57.5    57.5    58.7    59.4    63.1
  4086.6  4226.6  4316.6  4496.6  4526.6  4553.3  4673.3  4701.8  4741.5  4778.3
  4843.2  4915.5  4975.2  4981.2 4993.01  4993.1 5011.19  5011.3  5013.3  5020.5
  5035.6  5076.4  5131.7  5146.9  5189.2  5202.6  5203.7  5211.5  5218.7  5248.7
  5268.7  5288.7  5308.7  5328.7  5398.7  5458.7  5568.7  5591.4  5661.4  5671.4
  5681.4  5701.4  5715.4  5765.4  5815.4  5875.4  5965.4  5985.4  6005.4  6045.4
  6105.4  6145.4  6285.4  6465.4  6735.4  6775.4  6900.7  6950.7  6960.7  6970.7
      60    59.5    59.7      59    59.2   59.15   58.35   58.16    57.9   58.17
   58.09   58.02   58.08   58.09   58.11   58.11    58.1    58.1    58.1    58.1
   58.08   58.04   57.95   57.92   57.84   57.82   57.82    57.8   57.81   57.83
   57.84   57.86   57.87   57.89   57.94   57.99   58.07   58.08    58.1    58.1
    58.1    58.1    58.1    58.1   58.15   58.21   58.31   58.33   58.36    58.4
   58.36   58.33   58.24   58.11   57.93    57.9   57.82    58.7    59.4    63.1
   59.91   59.41   59.61   58.91   59.11   57.81   57.51   56.51      57   57.46
    57.8   57.57   56.89   56.05    50.5   55.82   55.81   50.82   52.06   55.56
   57.01    57.4   57.34   57.52   57.19      57   56.79   57.09   57.31   56.91
   57.51   56.71   57.21   56.41   56.51   57.21   57.01   57.61   57.21   56.71
   57.21   56.71   57.11   57.51   56.21   57.21   57.31   57.61   57.41   57.61
   57.51   57.11   57.81   57.51   57.81   57.41   57.41   58.61   59.31   63.01
BR Coef= 1 , 1 , 0 ,1.25, 0 ,,,.8,0,2,0,
WSPro=,,,, 1 ,,,, 0 ,,,, 0 ,,,,-1 ,-1 ,-1 , 0 , 0 , 0 , 0 , 0
BR U #Sta/Elev= 98
  4086.6      60  4226.6    59.5  4286.6    59.5  4316.6    59.7  4496.6      59
  4526.6    59.2  4531.5   58.96  4553.3    57.9  4593.3    57.9  4673.3    57.6
  4701.8    56.6  4741.5   57.09  4778.3   57.55  4778.7   57.55  4778.9    57.5
  4843.2   57.89  4859.1   57.72  4860.1   57.72  4912.2   57.66  4915.5   57.66
    4931   57.35  4931.8   57.34  4965.7      57  4975.2   56.98  4981.2   56.14
  4990.7   51.78  4992.9   50.65 4993.01   50.59  4993.1   50.55  4993.9   50.14
 4993.99   50.09  4994.1   50.03 4994.21   49.98  4995.9   49.11    4996   48.39
  4998.2   47.74  4999.6   47.47  5008.1   48.92  5010.9   50.66 5011.19   50.84
  5011.3   50.91  5013.3   52.15 5016.89    53.9    5017   53.95 5017.11      54
  5020.5   55.65  5027.3   56.34  5035.6    57.1  5076.4   57.49  5079.8   57.48
  5096.4   57.46  5131.7   57.43  5146.9   57.61  5189.2   57.28  5202.6   57.09
  5202.8   57.05  5203.7   56.88  5208.7    57.1  5211.5   57.18  5218.7    57.4
  5248.7      57  5268.7    57.6  5288.7    56.8  5308.7    57.3  5328.7    56.5
  5398.7    56.6  5458.7    57.3  5568.7    57.1  5591.4    57.7  5611.5   57.59
  5661.4    57.3  5671.4    56.8  5681.4    57.3  5701.4    56.8  5715.4    57.2
  5765.4    57.6    5774   57.38  5815.4    56.3  5875.4    57.3  5925.4    57.3
  5965.4    57.4  5985.4    57.7  6005.4    57.5    6044   57.69  6045.4    57.7
  6105.4    57.6  6145.4    57.2  6285.4    57.9  6335.4    57.7  6465.4    57.6
  6715.4    57.8  6735.4    57.9  6775.4    57.5  6900.7    57.5    6928   58.16
  6950.7    58.7  6960.7    59.4  6970.7    63.1
BR U #Mann= 3
  4086.6      .1  4981.2     .04  5020.5      .1
BR U Banks=4981.2,5020.5
BR D #Sta/Elev= 98
  4086.6   59.91  4226.6   59.41  4286.6   59.41  4316.6   59.61  4496.6   58.91
  4526.6   59.11  4531.5   58.87  4553.3   57.81  4593.3   57.81  4673.3   57.51
  4701.8   56.51  4741.5      57  4778.3   57.46  4778.7   57.46  4778.9   57.41
  4843.2    57.8  4859.1   57.63  4860.1   57.63  4912.2   57.57  4915.5   57.57
    4931   57.26  4931.8   57.25  4965.7   56.91  4975.2   56.89  4981.2   56.05
  4990.7   51.69  4992.9   50.56 4993.01    50.5  4993.1   50.46  4993.9   50.05
 4993.99      50  4994.1   49.94 4994.21   49.89  4995.9   49.02    4996    48.3
  4998.2   47.65  4999.6   47.38  5008.1   48.83  5010.9   50.57 5011.19   50.75
  5011.3   50.82  5013.3   52.06 5016.89   53.81    5017   53.86 5017.11   53.91
  5020.5   55.56  5027.3   56.25  5035.6   57.01  5076.4    57.4  5079.8   57.39
  5096.4   57.37  5131.7   57.34  5146.9   57.52  5189.2   57.19  5202.6      57
  5202.8   56.96  5203.7   56.79  5208.7   57.01  5211.5   57.09  5218.7   57.31
  5248.7   56.91  5268.7   57.51  5288.7   56.71  5308.7   57.21  5328.7   56.41
  5398.7   56.51  5458.7   57.21  5568.7   57.01  5591.4   57.61  5611.5    57.5
  5661.4   57.21  5671.4   56.71  5681.4   57.21  5701.4   56.71  5715.4   57.11
  5765.4   57.51    5774   57.29  5815.4   56.21  5875.4   57.21  5925.4   57.21
  5965.4   57.31  5985.4   57.61  6005.4   57.41    6044    57.6  6045.4   57.61
  6105.4   57.51  6145.4   57.11  6285.4   57.81  6335.4   57.61  6465.4   57.51
  6715.4   57.71  6735.4   57.81  6775.4   57.41  6900.7   57.41    6928   58.07
  6950.7   58.61  6960.7   59.31  6970.7   63.01
BR D #Mann= 3
  4086.6      .1  4981.2     .04  5020.5      .1
BR D Banks=4981.2,5020.5
BC Design=,, 0 ,, 0 ,,,,,,

Type RM Length L Ch R = 1 ,5776.6  ,148.1,148.1,148.1
BEGIN DESCRIPTION:
Downstream Section of Bridge/Culvert/Weir
END DESCRIPTION:
XS GIS Cut Line= 4
       3135791.8     13885138.74      3135291.07     13885126.45
      3134175.61     13885077.95      3132910.06     13885023.71
#Sta/Elev= 30
  4086.6   59.89  4526.6   59.09  4553.3   57.79  4673.3   57.49  4701.8   56.49
  4843.2   57.78  4915.5   57.55  4975.2   56.87  4981.2   56.03  4995.9      49
    4996   48.28  4999.6   47.36  5008.1   48.81  5020.5   55.54  5035.6   56.99
  5146.9    57.5  5203.7   56.77  5268.7   57.49  5328.7   56.39  5458.7   57.19
  5568.7   56.99  5591.4   57.59  5701.4   56.69  5765.4   57.49  5815.4   56.19
  5875.4   57.19  5985.4   57.59  6900.7   57.39  6960.7   59.29  6970.7   62.99
#Mann= 3 , 1 , 0
  4086.6      .1       0  4981.2     .04       0  5020.5      .1       0
#XS Ineff= 2 , 0
       0  4971.2    57.4  5030.5       0    57.4
Permanent Ineff=
       F       F
Bank Sta=4981.2,5020.5
XS Rating Curve= 0
Exp/Cntr=.5,.3

Type RM Length L Ch R = 1 ,5628.5  ,114.7,118.9,122.5
BEGIN DESCRIPTION:
Cross Section 5628.5-Interpolated
END DESCRIPTION:
XS GIS Cut Line= 4
       3136035.6     13885032.75      3135021.85     13884967.35
      3133266.77      13884896.3      3132853.13     13884969.29
#Sta/Elev= 30
  3824.7    60.5  3984.7    59.2  4334.7    59.5  4840.5      57  4880.5      58
  4900.5    57.4  4960.5    57.5  4970.5    55.6  4984.7   54.05  4994.7   47.39
  5005.3   47.07  5024.3   55.76  5060.5    58.1  5570.5    58.5  5610.5    57.4
  5650.5    58.2  5680.5    57.3  5770.5    57.1  5850.5    58.4  5960.5    58.7
  6050.5    57.6  6160.5    57.6  6250.5    58.5  6420.5      58  6470.5    58.5
  6580.5    57.5  6677.1    57.8  6737.1      59  6927.1    58.5  7017.1    63.9
#Mann= 3 , 1 , 0
  3824.7      .1       0  4984.7     .04       0  5024.3      .1       0
Bank Sta=4984.7,5024.3
XS Rating Curve= 0
Exp/Cntr=.5,.3

Type RM Length L Ch R = 1 ,5509.6  ,50,50,50
BEGIN DESCRIPTION:
Upstream Section of Bridge/Culvert/Weir
END DESCRIPTION:
XS GIS Cut Line= 4
      3135582.47     13884893.44      3135321.73      13884873.2
      3134152.27     13884821.23      3132769.97     13884762.07
#Sta/Elev= 30
  4247.1   58.82  4427.1   59.12  4633.4   56.72  4703.4   57.42  4743.4   56.82
  4821.4   57.38 4971.42   57.07 4980.73   56.58 4984.68   55.61 4995.02   48.95
 5002.26   47.82 5004.42   46.83 5004.98   48.63 5022.84   57.32 5041.08   57.88
 5228.98   56.98  5300.6   57.62  5682.7   56.22  5732.7   57.12  5892.7   57.62
  6042.7   57.12  6242.7   57.82  6352.7   56.92  6382.7   57.52  6632.7   57.72
  6742.7   57.12  6762.7   57.62  6912.8   57.62  6982.8   56.72  7062.8   60.22
#Mann= 3 , 1 , 0
  4247.1      .1       0 4984.68     .04       0 5022.84      .1       0
#XS Ineff= 2 , 0
       0  4974.7      58    5033       0    57.5
Permanent Ineff=
       F       F
Bank Sta=4984.68,5022.84
XS Rating Curve= 0
Exp/Cntr=.5,.3

Type RM Length L Ch R = 2 ,5484.6  ,,,
BEGIN DESCRIPTION:
ROSEMARY LANE, SKEW ANGLE OF 20 DEGREES
Structure ID: P84-9
END DESCRIPTION:
Bridge Culvert--1,0,-1,-1, 0
Deck Dist Width WeirC Skew NumUp NumDn MinLoCord MaxHiCord MaxSubmerge Is_Ogee
10,30,3,0, 60, 60, , , .95, 0, 1,1,,
  4247.1  4427.1  4465.3  4553.4  4593.4  4605.3  4633.4  4653.4  4703.4  4743.4
  4821.4 4825.54 4934.95 4948.11 4971.42 4980.73 4984.68 4985.59  4985.7 4995.02
 5002.26 5004.42 5004.98 5022.84  5025.9 5026.01 5041.08 5061.19 5123.99 5205.95
 5223.72 5228.98  5240.6  5270.6  5300.6  5350.6  5420.6  5590.9  5682.7  5732.7
  5812.7  5892.7  5942.7  6042.7  6082.7  6202.7  6242.7  6352.7  6382.7  6472.7
  6632.7  6682.7  6742.7  6762.7  6802.7  6892.7  6912.8  6982.8  7006.7  7062.8
    58.8    59.1    59.1   58.41   58.09      58   58.02   58.03   58.05   58.07
   58.11   58.11   58.21   58.22   58.25   58.25   58.26   58.26   58.76   58.81
   58.85   58.86   58.86   58.92   58.93   58.43   58.45   58.46   58.43   58.15
   58.07   58.05   58.02   58.02   58.02   58.01   58.01   57.97   57.94   57.92
    57.9   57.87   57.85   57.82   57.81   57.77   57.81   57.72   57.71   57.68
   57.71   57.61   57.59   57.61   57.57   57.54   57.61   57.51   57.76    60.2
    58.8    59.1   58.65    57.8      57   56.91    56.7    57.3    57.4    56.8
   57.36   57.18   57.16   56.93   57.05   56.56   55.59      55   54.93   48.93
    47.8   46.81   48.61    57.3   57.39    57.4   57.86   57.68    57.4   57.26
   57.13   56.96    57.3    57.1    57.6    57.5    57.3    56.3    56.2    57.1
    57.2    57.6    57.2    57.1    57.3    57.5    57.8    56.9    57.5    57.4
    57.7    57.6    57.1    57.6    57.3    57.4    57.6    56.7   57.75    60.2
  4247.1  4427.1  4465.3  4553.4  4593.4  4605.3  4633.4  4653.4  4703.4  4743.4
  4821.4 4825.54 4934.95 4948.11 4971.42 4980.73 4984.68 4985.59  4985.7 4995.02
 5002.26 5004.42 5004.98 5022.84  5025.9 5026.01 5041.08 5061.19 5123.99 5205.95
 5223.72 5228.98  5240.6  5270.6  5300.6  5350.6  5420.6  5590.9  5682.7  5732.7
  5812.7  5892.7  5942.7  6042.7  6082.7  6202.7  6242.7  6352.7  6382.7  6472.7
  6632.7  6682.7  6742.7  6762.7  6802.7  6892.7  6912.8  6982.8  7006.7  7062.8
    58.8    59.1    59.1   58.41   58.09      58   58.02   58.03   58.05   58.07
   58.11   58.11   58.21   58.22   58.25   58.25   58.26   58.26   58.76   58.81
   58.85   58.86   58.86   58.92   58.93   58.43   58.45   58.46   58.43   58.15
   58.07   58.05   58.02   58.02   58.02   58.01   58.01   57.97   57.94   57.92
    57.9   57.87   57.85   57.82   57.81   57.77   57.81   57.72   57.71   57.68
   57.71   57.61   57.59   57.61   57.57   57.54   57.61   57.51   57.76    60.2
   58.79   59.09   58.64   57.79   56.99    56.9   56.69   57.29   57.39   56.79
   57.35   57.17   57.15   56.92   57.04   56.55   55.58   54.99   54.92   48.92
   47.79    46.8    48.6   57.29   57.38   57.39   57.85   57.67   57.39   57.25
   57.12   56.95   57.29   57.09   57.59   57.49   57.29   56.29   56.19   57.09
   57.19   57.59   57.19   57.09   57.29   57.49   57.79   56.89   57.49   57.39
   57.69   57.59   57.09   57.59   57.29   57.39   57.59   56.69   57.74   60.19
BR Coef= 1 , 0 , 0 ,1.25, 0 ,,,.8,-1,2,0,
WSPro=,,,, 1 ,,,, 0 ,,,, 0 ,,,,-1 ,-1 ,-1 , 0 , 0 , 0 , 0 , 0
Culvert=2,10,10.3,30,.015,.4,1,8,1,46.8,5000.7,46.77,5000.7,Culvert #1  , 0 ,10
Culvert Bottom n=.015
BR U #Sta/Elev= 74
  4247.1    58.8  4327.1    58.9  4427.1    59.1  4465.3   58.65  4487.1    58.4
  4553.4    57.8  4593.4      57  4605.3   56.91  4633.4    56.7  4653.4    57.3
  4703.4    57.4  4743.4    56.8  4790.5   57.08  4793.4    57.1  4821.4   57.36
 4825.54   57.18  4862.3   57.22 4868.12   57.23 4934.95   57.16 4948.11   56.93
 4971.42   57.05 4980.73   56.56 4984.68   55.59 4985.59      55  4985.7   54.93
 4985.81   54.86 4995.02   48.93 5002.26    47.8 5004.42   46.81 5004.98   48.61
  5014.8   53.39 5022.84    57.3 5025.79   57.39  5025.9   57.39 5026.01    57.4
 5041.08   57.86  5050.3   57.78 5061.19   57.68 5123.99    57.4  5141.8   57.43
 5142.22   57.43 5205.95   57.26 5223.72   57.13 5228.98   56.96  5236.7   57.19
  5240.6    57.3  5270.6    57.1  5300.6    57.6  5350.6    57.5  5420.6    57.3
  5505.3    56.8  5590.9    56.3  5682.7    56.2  5732.7    57.1  5812.7    57.2
  5892.7    57.6  5942.7    57.2  6042.7    57.1  6082.7    57.3  6202.7    57.5
  6242.7    57.8  6352.7    56.9  6382.7    57.5  6472.7    57.4  6632.7    57.7
  6682.7    57.6  6742.7    57.1  6762.7    57.6  6802.7    57.3  6892.7    57.4
  6912.8    57.6  6982.8    56.7  7006.7   57.75  7062.8    60.2
BR U #Mann= 3
  4247.1      .1 4984.68     .04 5022.84      .1
BR U Banks=4984.68,5022.84
BR D #Sta/Elev= 74
  4247.1   58.79  4327.1   58.89  4427.1   59.09  4465.3   58.64  4487.1   58.39
  4553.4   57.79  4593.4   56.99  4605.3    56.9  4633.4   56.69  4653.4   57.29
  4703.4   57.39  4743.4   56.79  4790.5   57.07  4793.4   57.09  4821.4   57.35
 4825.54   57.17  4862.3   57.21 4868.12   57.22 4934.95   57.15 4948.11   56.92
 4971.42   57.04 4980.73   56.55 4984.68   55.58 4985.59   54.99  4985.7   54.92
 4985.81   54.85 4995.02   48.92 5002.26   47.79 5004.42    46.8 5004.98    48.6
  5014.8   53.38 5022.84   57.29 5025.79   57.38  5025.9   57.38 5026.01   57.39
 5041.08   57.85  5050.3   57.77 5061.19   57.67 5123.99   57.39  5141.8   57.42
 5142.22   57.42 5205.95   57.25 5223.72   57.12 5228.98   56.95  5236.7   57.18
  5240.6   57.29  5270.6   57.09  5300.6   57.59  5350.6   57.49  5420.6   57.29
  5505.3   56.79  5590.9   56.29  5682.7   56.19  5732.7   57.09  5812.7   57.19
  5892.7   57.59  5942.7   57.19  6042.7   57.09  6082.7   57.29  6202.7   57.49
  6242.7   57.79  6352.7   56.89  6382.7   57.49  6472.7   57.39  6632.7   57.69
  6682.7   57.59  6742.7   57.09  6762.7   57.59  6802.7   57.29  6892.7   57.39
  6912.8   57.59  6982.8   56.69  7006.7   57.74  7062.8   60.19
BR D #Mann= 3
  4247.1      .1 4984.68     .04 5022.84      .1
BR D Banks=4984.68,5022.84
BC Design=,, 0 ,, 0 ,,,,,,

Type RM Length L Ch R = 1 ,5459.6  ,165.2,165.2,165.2
BEGIN DESCRIPTION:
Downstream Section of Bridge/Culvert/Weir
END DESCRIPTION:
XS GIS Cut Line= 4
      3135569.74     13884845.09      3135309.01     13884824.84
      3134139.55     13884772.87      3132757.25     13884713.72
#Sta/Elev= 30
  4247.1   58.79  4427.1   59.09  4633.4   56.69  4703.4   57.39  4743.4   56.79
  4821.4   57.35 4971.42   57.04 4980.73   56.55 4984.68   55.58 4995.02   48.92
 5002.26   47.79 5004.42    46.8 5004.98    48.6 5022.84   57.29 5041.08   57.85
 5228.98   56.95  5300.6   57.59  5682.7   56.19  5732.7   57.09  5892.7   57.59
  6042.7   57.09  6242.7   57.79  6352.7   56.89  6382.7   57.49  6632.7   57.69
  6742.7   57.09  6762.7   57.59  6912.8   57.59  6982.8   56.69  7062.8   60.19
#Mann= 3 , 1 , 0
  4247.1      .1       0 4984.68     .04       0 5022.84      .1       0
#XS Ineff= 2 , 0
       0  4974.7    57.9    5033       0    57.4
Permanent Ineff=
       F       F
Bank Sta=4984.68,5022.84
XS Rating Curve= 0
Exp/Cntr=.5,.3

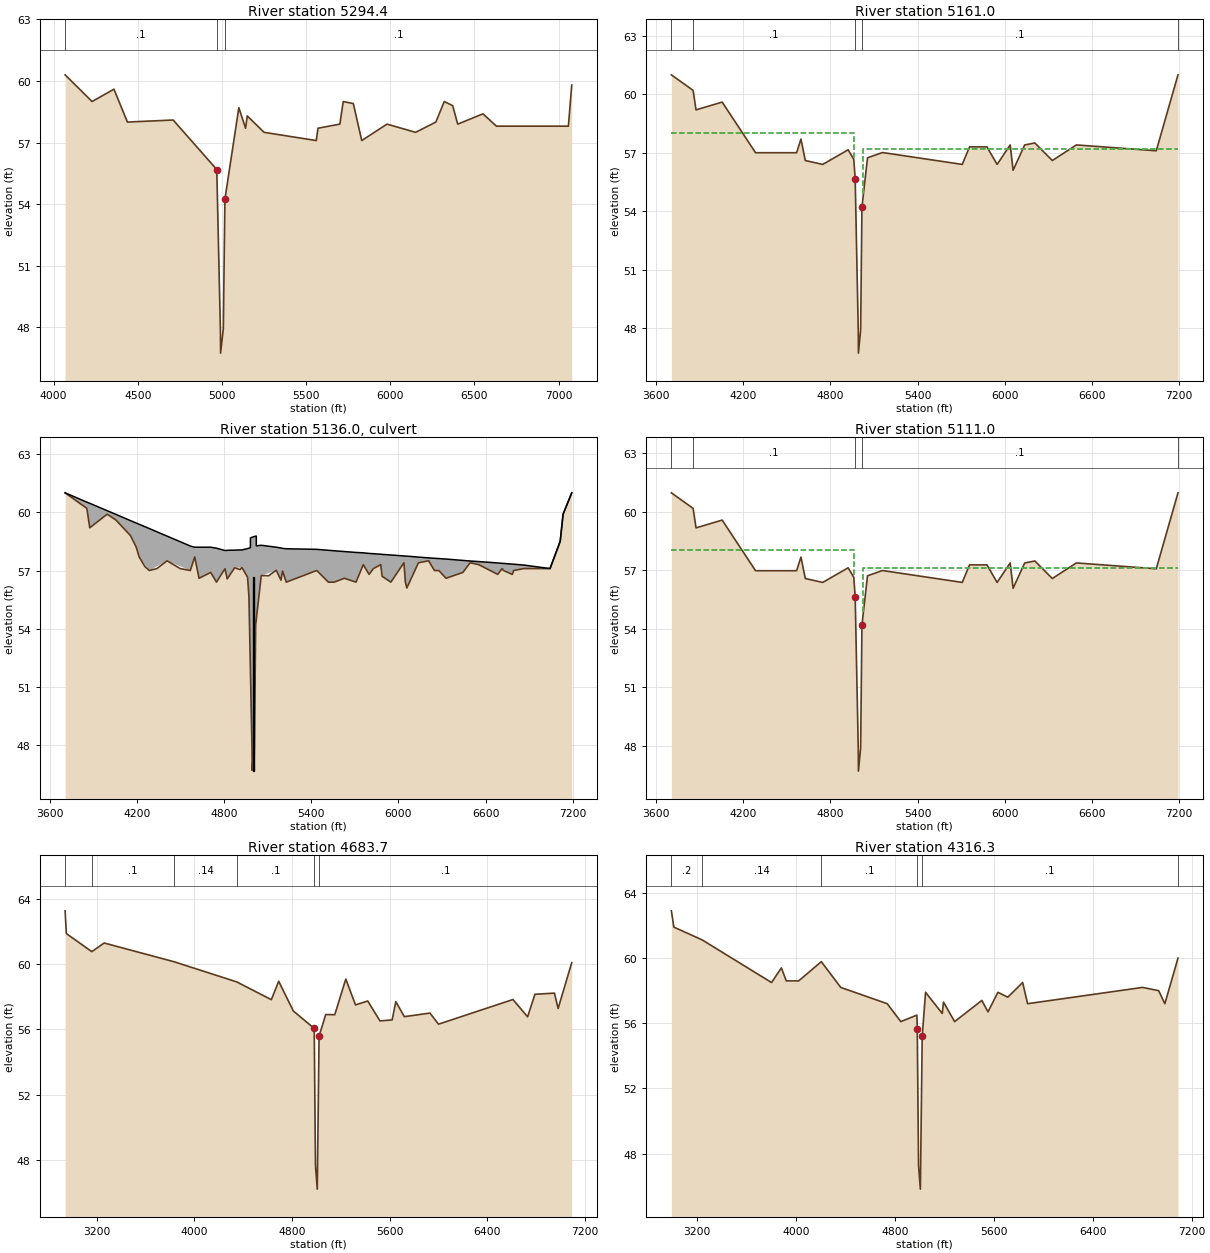
Type RM Length L Ch R = 1 ,5294.4  ,121.4,133.4,145.8
BEGIN DESCRIPTION:
Cross Section 5294.4-Interpolated
END DESCRIPTION:
XS GIS Cut Line= 4
      3135705.17     13884663.56      3135291.86      13884647.6
       3132936.8     13884607.05      3132718.63     13884706.75
#Sta/Elev= 30
  4068.9    60.3  4228.9      59  4358.9    59.6  4438.9      58  4710.6    58.1
  4969.6   55.69  4991.4   47.77  4992.2   46.75  5008.5   47.94  5017.9   54.24
  5100.6    58.7  5140.6    57.7  5150.6    58.3  5250.6    57.5  5560.6    57.1
  5570.6    57.7  5700.6    57.9  5720.6      59  5780.6    58.9  5830.6    57.1
  5980.6    57.9  6150.6    57.5  6270.6      58  6320.6      59  6370.6    58.8
  6400.6    57.9  6550.6    58.4  6630.6    57.8  7057.8    57.8  7077.8    59.8
#Mann= 3 , 1 , 0
  4068.9      .1       0  4969.6     .04       0  5017.9      .1       0
Bank Sta=4969.6,5017.9
XS Rating Curve= 0
Exp/Cntr=.5,.3

Type RM Length L Ch R = 1 ,5161.0  ,50,50,50
BEGIN DESCRIPTION:
Upstream Section of Bridge/Culvert/Weir
END DESCRIPTION:
XS GIS Cut Line= 6
       3136032.8     13884572.19      3135460.95     13884550.54
       3134417.2     13884502.67      3133343.69     13884457.99
      3132766.15     13884433.06      3132547.69     13884430.26
#Sta/Elev= 30
  3704.9      61  3854.6    60.2  3874.6    59.2  4054.6    59.6  4284.6      57
    4567      57    4597    57.7    4627    56.6    4747    56.4 4921.98   57.15
  4960.9   56.66 4970.48   55.65 4991.92   47.73 4992.67   46.71 5007.99    47.9
 5016.83    54.2 5055.27   56.74 5158.58   57.01  5707.6    56.4  5757.6    57.3
  5877.6    57.3  5947.6    56.4  6037.6    57.4  6057.6    56.1  6137.6    57.4
  6207.6    57.5  6327.6    56.6  6493.4    57.4  7043.4    57.1    7193      61
#Mann= 5 , 1 , 0
  3704.9      .2       0  3854.6      .1       0 4970.48     .04       0
 5016.83      .1       0    7193      .2       0
#XS Ineff= 2 , 0
       0  4960.4   58.02  5026.9       0    57.2
Permanent Ineff=
       F       F
Bank Sta=4970.48,5016.83
XS Rating Curve= 0
Exp/Cntr=.5,.3

Type RM Length L Ch R = 2 ,5136.0  ,,,
BEGIN DESCRIPTION:
CEDAR HILL LANE, SKEW ANGLE OF 20 DEGREES
Structure ID: P84-8,,,,
END DESCRIPTION:
Bridge Culvert--1,0,-1,-1, 0
Deck Dist Width WeirC Skew NumUp NumDn MinLoCord MaxHiCord MaxSubmerge Is_Ogee
10,30,3,0, 60, 60, , , .95, 0, 1,1,,
  3704.9  3854.6  3874.6  3994.6  4054.6  4154.6  4214.6  4284.6    4407    4567
    4597    4627    4707    4747 4805.42 4821.02 4872.54 4921.98  4960.9 4970.48
 4980.79  4980.9 4991.92 4992.67 4998.87 5006.11 5007.99 5016.83  5021.1 5021.21
 5055.27 5158.58  5191.1  5202.1  5227.7  5437.6  5517.6  5707.6  5757.6  5797.6
  5877.6  5887.6  5947.6  6037.6  6047.6  6057.6  6137.6  6207.6  6247.6  6327.6
  6443.4  6493.4  6683.4  6713.4  6783.4  6863.4  7043.4  7113.4  7133.4    7193
      61   60.52   60.46   60.08   59.89   59.57   59.38   59.16   58.77   58.26
    58.2    58.2    58.2   58.15   58.03   58.04   58.05   58.06   58.13   58.15
   58.18   58.68   58.71   58.71   58.73   58.75   58.75   58.77   58.77   58.27
    58.3    58.2   58.16   58.14   58.12   58.09   58.04   57.93   57.91   57.88
   57.84   57.83    57.8   57.75   57.74   57.74   57.69   57.65   57.63   57.59
   57.52   57.49   57.39   57.37   57.33   57.28    57.1    58.5    59.9      61
      61    60.2    59.2    59.9    59.6    58.8    57.7      57    57.5      57
    57.7    56.6    56.9    56.4   57.09   56.57   57.14   57.15   56.66   55.65
   51.84    51.8   47.73   46.71   47.32   47.32    47.9    54.2   54.48   54.49
   56.74   57.01    56.5   56.97    56.4      57    56.4    56.4    57.3    56.8
    57.3    56.7    56.4    57.4    56.4    56.1    57.4    57.5      57    56.6
    56.9    57.4    56.8    57.1    56.8    57.1    57.1    58.5    59.9      61
  3704.9  3854.6  3874.6  3994.6  4054.6  4154.6  4214.6  4284.6    4407    4567
    4597    4627    4707    4747 4805.42 4821.02 4872.54 4921.98  4960.9 4970.48
 4980.79  4980.9 4991.92 4992.67 4998.87 5006.11 5007.99 5016.83  5021.1 5021.21
 5055.27 5158.58  5191.1  5202.1  5227.7  5437.6  5517.6  5707.6  5757.6  5797.6
  5877.6  5887.6  5947.6  6037.6  6047.6  6057.6  6137.6  6207.6  6247.6  6327.6
  6443.4  6493.4  6683.4  6713.4  6783.4  6863.4  7043.4  7113.4  7133.4    7193
      61   60.52   60.46   60.08   59.89   59.57   59.38   59.16   58.77   58.26
    58.2    58.2    58.2   58.15   58.03   58.04   58.05   58.06   58.13   58.15
   58.18   58.68   58.71   58.71   58.73   58.75   58.75   58.77   58.77   58.27
    58.3    58.2   58.16   58.14   58.12   58.09   58.04   57.93   57.91   57.88
   57.84   57.83    57.8   57.75   57.74   57.74   57.69   57.65   57.63   57.59
   57.52   57.49   57.39   57.37   57.33   57.28    57.1    58.5    59.9      61
   60.99   60.19   59.19   59.89   59.59   58.79   57.69   56.99   57.49   56.99
   57.69   56.59   56.89   56.39   57.08   56.56   57.13   57.14   56.65   55.64
   51.83   51.79   47.72    46.7   47.31   47.31   47.89   54.19   54.47   54.48
   56.73      57   56.49   56.96   56.39   56.99   56.39   56.39   57.29   56.79
   57.29   56.69   56.39   57.39   56.39   56.09   57.39   57.49   56.99   56.59
   56.89   57.39   56.79   57.09   56.79   57.09   57.09   58.49   59.89   60.99
BR Coef= 1 , 0 , 0 ,1.25, 0 ,,,.8,-1,2,0,
WSPro=,,,, 1 ,,,, 0 ,,,, 0 ,,,,-1 ,-1 ,-1 , 0 , 0 , 0 , 0 , 0
Culvert=2,10,10.3,30,.015,.4,1,8,1,46.67,5000.6,46.64,5000.6,Culvert #1  , 0 ,10
Culvert Bottom n=.015
BR U #Sta/Elev= 88
  3704.9      61  3854.6    60.2  3874.6    59.2  3994.6    59.9  4054.6    59.6
  4154.6    58.8  4194.6    58.2  4214.6    57.7  4254.6    57.2  4284.6      57
    4337    57.1    4407    57.5    4497    57.1    4567      57  4587.2   57.47
    4597    57.7    4627    56.6    4707    56.9  4727.2   56.65    4747    56.4
  4789.8   56.91 4805.42   57.09 4812.47   56.86 4821.02   56.57    4867   57.08
 4872.54   57.14 4908.63   57.05 4921.98   57.15    4935   56.99  4960.9   56.66
 4970.48   55.65 4980.79   51.84  4980.9    51.8 4981.01   51.76 4991.92   47.73
 4992.67   46.71 4998.87   47.32 5006.11   47.32 5007.99    47.9    5010   49.33
 5016.83    54.2 5020.99   54.47  5021.1   54.48 5021.21   54.49 5055.27   56.74
  5072.3   56.74 5108.01   56.73 5118.16    56.8  5146.8   56.95 5158.58   57.01
  5191.1    56.5  5202.1   56.97  5216.3   56.65  5227.7    56.4    5412   56.93
  5437.6      57  5517.6    56.4  5557.6    56.4  5627.6    56.6  5707.6    56.4
  5757.6    57.3  5797.6    56.8  5827.6    57.1  5877.6    57.3  5887.6    56.7
  5947.6    56.4  6037.6    57.4  6047.6    56.4  6057.6    56.1  6137.6    57.4
  6207.6    57.5  6247.6      57  6277.6      57  6327.6    56.6  6443.4    56.9
  6493.4    57.4  6553.4    57.3  6683.4    56.8  6713.4    57.1  6723.4      57
  6783.4    56.8  6793.4      57  6863.4    57.1  7013.8    57.1  7043.4    57.1
  7113.4    58.5  7133.4    59.9    7193      61
BR U #Mann= 5
  3704.9      .2  3854.6      .1 4970.48     .04 5016.83      .1    7193      .2
BR U Banks=4970.48,5016.83
BR D #Sta/Elev= 88
  3704.9   60.99  3854.6   60.19  3874.6   59.19  3994.6   59.89  4054.6   59.59
  4154.6   58.79  4194.6   58.19  4214.6   57.69  4254.6   57.19  4284.6   56.99
    4337   57.09    4407   57.49    4497   57.09    4567   56.99  4587.2   57.46
    4597   57.69    4627   56.59    4707   56.89  4727.2   56.64    4747   56.39
  4789.8    56.9 4805.42   57.08 4812.47   56.85 4821.02   56.56    4867   57.07
 4872.54   57.13 4908.63   57.04 4921.98   57.14    4935   56.98  4960.9   56.65
 4970.48   55.64 4980.79   51.83  4980.9   51.79 4981.01   51.75 4991.92   47.72
 4992.67    46.7 4998.87   47.31 5006.11   47.31 5007.99   47.89    5010   49.32
 5016.83   54.19 5020.99   54.46  5021.1   54.47 5021.21   54.48 5055.27   56.73
  5072.3   56.73 5108.01   56.72 5118.16   56.79  5146.8   56.94 5158.58      57
  5191.1   56.49  5202.1   56.96  5216.3   56.64  5227.7   56.39    5412   56.92
  5437.6   56.99  5517.6   56.39  5557.6   56.39  5627.6   56.59  5707.6   56.39
  5757.6   57.29  5797.6   56.79  5827.6   57.09  5877.6   57.29  5887.6   56.69
  5947.6   56.39  6037.6   57.39  6047.6   56.39  6057.6   56.09  6137.6   57.39
  6207.6   57.49  6247.6   56.99  6277.6   56.99  6327.6   56.59  6443.4   56.89
  6493.4   57.39  6553.4   57.29  6683.4   56.79  6713.4   57.09  6723.4   56.99
  6783.4   56.79  6793.4   56.99  6863.4   57.09  7013.8   57.09  7043.4   57.09
  7113.4   58.49  7133.4   59.89    7193   60.99
BR D #Mann= 5
  3704.9      .2  3854.6      .1 4970.48     .04 5016.83      .1    7193      .2
BR D Banks=4970.48,5016.83
BC Design=,, 0 ,, 0 ,,,,,,

Type RM Length L Ch R = 1 ,5111.0  ,427.3,427.3,427.3
BEGIN DESCRIPTION:
Downstream Section of Bridge/Culvert/Weir
END DESCRIPTION:
XS GIS Cut Line= 6
      3136017.74     13884524.51      3135445.89     13884502.86
      3134402.14     13884454.99      3133328.63     13884410.31
      3132751.09     13884385.38      3132532.64     13884382.58
#Sta/Elev= 30
  3704.9   60.98  3854.6   60.18  3874.6   59.18  4054.6   59.58  4284.6   56.98
    4567   56.98    4597   57.68    4627   56.58    4747   56.38 4921.98   57.13
  4960.9   56.64 4970.48   55.63 4991.92   47.71 4992.67   46.69 5007.99   47.88
 5016.83   54.18 5055.27   56.72 5158.58   56.99  5707.6   56.38  5757.6   57.28
  5877.6   57.28  5947.6   56.38  6037.6   57.38  6057.6   56.08  6137.6   57.38
  6207.6   57.48  6327.6   56.58  6493.4   57.38  7043.4   57.08    7193   60.98
#Mann= 5 , 1 , 0
  3704.9      .2       0  3854.6      .1       0 4970.48     .04       0
 5016.83      .1       0    7193      .2       0
#XS Ineff= 2 , 0
       0  4960.4   58.02  5026.9       0    57.1
Permanent Ineff=
       F       F
Bank Sta=4970.48,5016.83
XS Rating Curve= 0
Exp/Cntr=.5,.3

Type RM Length L Ch R = 1 ,4683.7  ,394.9,367.4,259.9
BEGIN DESCRIPTION:
Cross Section 4683.7-Interpolated
END DESCRIPTION:
XS GIS Cut Line= 4
      3136641.13     13883784.21      3134740.88      13884026.8
      3134451.95     13884081.83      3132531.72     13884369.54
#Sta/Elev= 30
    2940   63.26    2950   61.87  3158.8   60.76    3260   61.29  3833.8   60.14
  4345.8   58.91    4630   57.82    4690   58.95    4810   57.13  4981.2   56.06
  4991.5   47.66  5006.2   46.22    5021   55.59  5075.7   56.91  5149.8    56.9
  5239.8   59.08  5319.8    57.5  5419.8   57.74  5519.8   56.52  5619.8   56.58
  5649.8    57.7  5719.8   56.78  5929.8      57  5999.8   56.32  6609.8   57.83
  6729.8   56.77  6789.8   58.15  6949.8   58.22  6979.8   57.28  7091.5   60.09
#Mann= 6 , 1 , 0
    2940      .2       0  3158.8      .1       0  3833.8     .14       0
  4345.8      .1       0  4981.2     .04       0    5021      .1       0
Bank Sta=4981.2,5021
XS Rating Curve= 0
Exp/Cntr=.3,.1

Type RM Length L Ch R = 1 ,4316.3  ,160.4,151.5,134.4
BEGIN DESCRIPTION:
Cross Section 4316.3-Interpolated
END DESCRIPTION:
XS GIS Cut Line= 5
      3136456.88     13883228.92      3135591.09     13883432.63
      3134754.24     13883612.88      3134380.87     13883741.63
      3132520.47     13884346.74
#Sta/Elev= 30
  2992.8    62.9  3012.8    61.9  3240.8   61.12  3802.8    58.5  3882.2    59.4
  3922.2    58.6  4022.2    58.6  4205.3   59.78  4362.2    58.2  4738.2    57.2
  4848.2    56.1  4978.2    56.5  4981.2   55.66  4991.5   47.26  5006.2   45.82
    5021   55.19  5048.2    57.9  5183.2    56.6  5193.2    57.3  5283.2    56.1
  5503.2    57.4  5553.2    56.7  5633.2    57.9  5713.2    57.6  5833.2    58.5
  5873.2    57.2  6803.2    58.2  6933.2      58  6983.2    57.2  7089.5      60
#Mann= 6 , 1 , 0
  2992.8      .2       0  3240.8     .14       0  4205.3      .1       0
  4981.2     .04       0    5021      .1       0  7089.5      .2       0
Bank Sta=4981.2,5021
XS Rating Curve= 0
Exp/Cntr=.5,.3

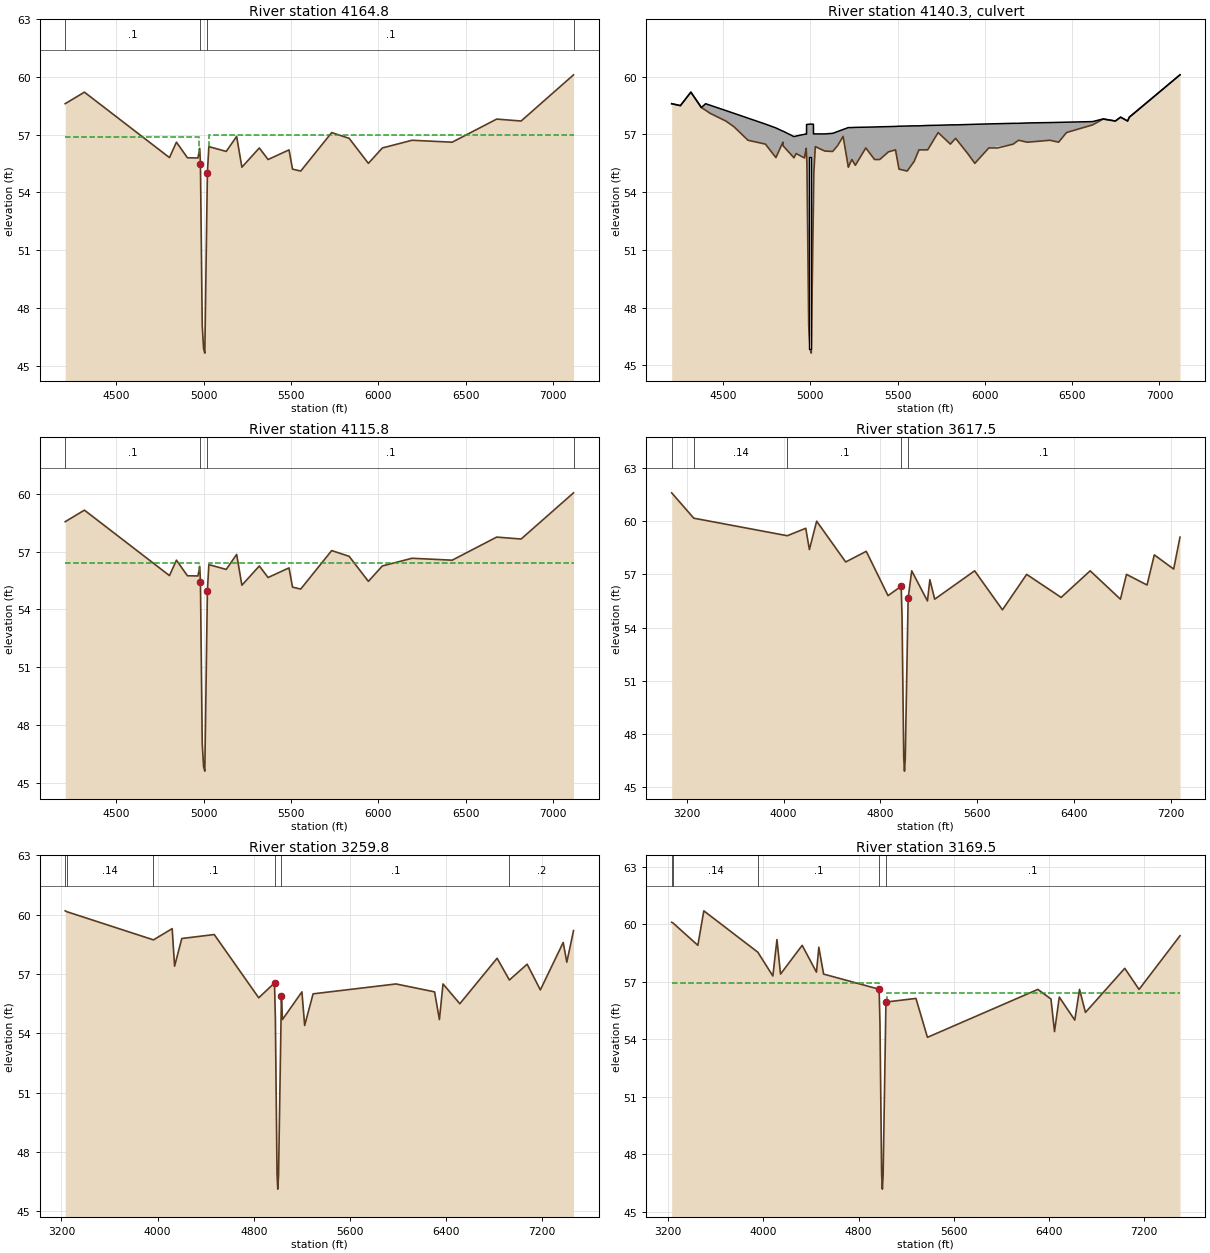
Type RM Length L Ch R = 1 ,4164.8  ,49,49,49
BEGIN DESCRIPTION:
Upstream Section of Bridge/Culvert/Weir
END DESCRIPTION:
XS GIS Cut Line= 6
      3135210.89     13883276.01      3134944.84     13883366.45
      3134594.07     13883498.49      3133886.15     13883763.09
      3133078.79     13884056.36       3132473.1     13884263.95
#Sta/Elev= 30
  4206.8   58.61  4316.8   59.21  4803.8   55.81  4843.8   56.61  4906.8    55.8
  4966.9   55.79  4977.1   56.29  4981.2   55.49  4991.5   47.09  4999.3   45.88
  5006.2   45.65    5021   55.02  5029.4   56.38  5128.9   56.13  5188.5   56.91
  5218.5   55.31  5318.5   56.31  5368.5   55.71  5488.5   56.21  5508.5   55.21
  5555.4   55.11  5732.8   57.11  5832.8   56.81  5942.8   55.51  6022.8   56.31
  6192.8   56.71  6422.8   56.61  6677.5   57.81  6817.5   57.71  7117.6   60.11
#Mann= 4 , 1 , 0
  4206.8      .1       0  4981.2     .04       0    5021      .1       0
  7117.6      .2       0
#XS Ineff= 2 , 0
       0  4971.2    56.9    5031       0      57
Permanent Ineff=
       F       F
Bank Sta=4981.2,5021
XS Rating Curve= 0
Exp/Cntr=.5,.3

Type RM Length L Ch R = 2 ,4140.3  ,,,
BEGIN DESCRIPTION:
LONE OAK ROAD
Structure ID: P84-6
END DESCRIPTION:
Bridge Culvert--1,0,-1,-1, 0
Deck Dist Width WeirC Skew NumUp NumDn MinLoCord MaxHiCord MaxSubmerge Is_Ogee
10,29,3,0, 60, 60, , , .95, 0, 1,1,,
  4206.8  4256.8  4316.8  4376.8  4400.9  4563.8  4643.8  4743.8  4803.8  4843.8
  4845.2  4906.8  4919.6  4966.9  4977.1 4978.99  4979.1  4981.2  4991.5  4999.3
  5006.2  5009.2  5018.7 5018.81    5021  5029.4  5083.5  5128.9  5188.5  5218.5
  5238.5  5258.5  5318.5  5368.5  5398.5  5448.5  5488.5  5508.5  5555.4  5595.4
  5622.8  5672.8  5732.8  5802.8  5832.8  5942.8  6022.8  6162.8  6192.8  6242.8
  6372.8  6422.8  6467.5  6617.5  6677.5  6747.5  6777.5  6817.5  6827.5  7117.6
    58.6    58.5    59.2    58.4    58.6    58.1   57.85   57.54   57.34   57.17
   57.17   56.89   56.92   57.01   57.02   57.02   57.52   57.52   57.53   57.54
   57.54   57.54   57.53   57.03   57.03   57.03   57.03   57.06   57.26   57.36
   57.36   57.37   57.38   57.39    57.4   57.41   57.42   57.43   57.44   57.45
   57.45   57.47   57.48    57.5    57.5   57.53   57.55   57.58   57.58    57.6
   57.62   57.63   57.64   57.67   57.81    57.7    57.9    57.7    57.9    60.1
    58.6    58.5    59.2    58.4   58.26    57.4    56.7    56.5    55.8    56.6
   56.41   55.79   56.01   55.78   56.28   55.91   55.89   55.48   47.08   45.87
   45.64   47.64   53.57   53.64   55.01   56.37   56.14   56.12    56.9    55.3
    55.7    55.4    56.3    55.7    55.7    56.1    56.2    55.2    55.1    55.6
    56.2    56.2    57.1    56.5    56.8    55.5    56.3    56.5    56.7    56.6
    56.7    56.6    57.1    57.5    57.8    57.7    57.9    57.7    57.9    60.1
  4206.8  4256.8  4316.8  4376.8  4400.9  4563.8  4643.8  4743.8  4803.8  4843.8
  4845.2  4906.8  4919.6  4966.9  4977.1 4978.99  4979.1  4981.2  4991.5  4999.3
  5006.2  5009.2  5018.7 5018.81    5021  5029.4  5083.5  5128.9  5188.5  5218.5
  5238.5  5258.5  5318.5  5368.5  5398.5  5448.5  5488.5  5508.5  5555.4  5595.4
  5622.8  5672.8  5732.8  5802.8  5832.8  5942.8  6022.8  6162.8  6192.8  6242.8
  6372.8  6422.8  6467.5  6617.5  6677.5  6747.5  6777.5  6817.5  6827.5  7117.6
    58.6    58.5    59.2    58.4    58.6    58.1   57.85   57.54   57.34   57.17
   57.17   56.89   56.92   57.01   57.02   57.02   57.52   57.52   57.53   57.54
   57.54   57.54   57.53   57.03   57.03   57.03   57.03   57.06   57.26   57.36
   57.36   57.37   57.38   57.39    57.4   57.41   57.42   57.43   57.44   57.45
   57.45   57.47   57.48    57.5    57.5   57.53   57.55   57.58   57.58    57.6
   57.62   57.63   57.64   57.67   57.81    57.7    57.9    57.7    57.9    60.1
   58.55   58.45   59.15   58.35   58.21   57.35   56.65   56.45   55.75   56.55
   56.36   55.74   55.96   55.73   56.23   55.86   55.84   55.43   47.03   45.82
   45.59   47.59   53.52   53.59   54.96   56.32   56.09   56.07   56.85   55.25
   55.65   55.35   56.25   55.65   55.65   56.05   56.15   55.15   55.05   55.55
   56.15   56.15   57.05   56.45   56.75   55.45   56.25   56.45   56.65   56.55
   56.65   56.55   57.05   57.45   57.75   57.65   57.85   57.65   57.85   60.05
BR Coef= 1 , 0 , 0 ,1.25, 0 ,,,.8,-1,2,0,
WSPro=,,,, 1 ,,,, 0 ,,,, 0 ,,,,-1 ,-1 ,-1 , 0 , 0 , 0 , 0 , 0
Culvert=2,10,10,29,.015,.4,1,8,1,45.85,4999.4,45.83,4999.4,Culvert #1  , 0 ,10
Culvert Bottom n=.015
BR U #Sta/Elev= 81
  4206.8    58.6  4256.8    58.5  4316.8    59.2  4376.8    58.4  4400.9   58.26
  4426.8    58.1  4516.8    57.7  4563.8    57.4  4643.8    56.7  4693.8    56.6
  4743.8    56.5  4791.4   55.94  4803.8    55.8  4843.8    56.6  4844.3   56.53
  4845.2   56.41  4906.8   55.79    4907   55.79  4919.6   56.01  4965.2   55.79
  4966.9   55.78  4977.1   56.28 4978.99   55.91  4979.1   55.89 4979.21   55.87
  4981.2   55.48  4990.7   47.72  4991.5   47.08  4999.3   45.87  5001.6   45.79
  5006.2   45.64  5009.2   47.64 5018.59    53.5  5018.7   53.57 5018.81   53.64
    5021   55.01  5029.4   56.37  5050.3   56.28  5083.5   56.14  5122.2   56.12
  5128.9   56.12  5157.6   56.43  5188.5    56.9    5217   55.38  5218.5    55.3
  5238.5    55.7  5258.5    55.4  5318.5    56.3  5368.5    55.7  5398.5    55.7
  5448.5    56.1  5488.5    56.2  5508.5    55.2  5555.4    55.1  5595.4    55.6
  5622.8    56.2  5672.8    56.2  5732.8    57.1  5802.8    56.5  5832.8    56.8
  5902.8      56  5942.8    55.5  5992.8      56  6022.8    56.3  6072.8    56.3
  6162.8    56.5  6192.8    56.7  6242.8    56.6  6258.3   56.61  6372.8    56.7
  6422.8    56.6  6467.5    57.1  6617.5    57.5  6677.5    57.8  6747.5    57.7
  6766.8   57.83  6777.5    57.9  6817.5    57.7  6827.5    57.9  6867.5    58.2
  7117.6    60.1
BR U #Mann= 4
  4206.8      .1  4981.2     .04    5021      .1  7117.6      .2
BR U Banks=4981.2,5021
BR D #Sta/Elev= 81
  4206.8   58.55  4256.8   58.45  4316.8   59.15  4376.8   58.35  4400.9   58.21
  4426.8   58.05  4516.8   57.65  4563.8   57.35  4643.8   56.65  4693.8   56.55
  4743.8   56.45  4791.4   55.89  4803.8   55.75  4843.8   56.55  4844.3   56.48
  4845.2   56.36  4906.8   55.74    4907   55.74  4919.6   55.96  4965.2   55.74
  4966.9   55.73  4977.1   56.23 4978.99   55.86  4979.1   55.84 4979.21   55.82
  4981.2   55.43  4990.7   47.67  4991.5   47.03  4999.3   45.82  5001.6   45.74
  5006.2   45.59  5009.2   47.59 5018.59   53.45  5018.7   53.52 5018.81   53.59
    5021   54.96  5029.4   56.32  5050.3   56.23  5083.5   56.09  5122.2   56.07
  5128.9   56.07  5157.6   56.38  5188.5   56.85    5217   55.33  5218.5   55.25
  5238.5   55.65  5258.5   55.35  5318.5   56.25  5368.5   55.65  5398.5   55.65
  5448.5   56.05  5488.5   56.15  5508.5   55.15  5555.4   55.05  5595.4   55.55
  5622.8   56.15  5672.8   56.15  5732.8   57.05  5802.8   56.45  5832.8   56.75
  5902.8   55.95  5942.8   55.45  5992.8   55.95  6022.8   56.25  6072.8   56.25
  6162.8   56.45  6192.8   56.65  6242.8   56.55  6258.3   56.56  6372.8   56.65
  6422.8   56.55  6467.5   57.05  6617.5   57.45  6677.5   57.75  6747.5   57.65
  6766.8   57.78  6777.5   57.85  6817.5   57.65  6827.5   57.85  6867.5   58.15
  7117.6   60.05
BR D #Mann= 4
  4206.8      .1  4981.2     .04    5021      .1  7117.6      .2
BR D Banks=4981.2,5021
BC Design=,, 0 ,, 0 ,,,,,,

Type RM Length L Ch R = 1 ,4115.8  ,498.3,498.3,498.3
BEGIN DESCRIPTION:
Downstream Section of Bridge/Culvert/Weir
END DESCRIPTION:
XS GIS Cut Line= 6
      3135197.93     13883228.75      3134931.88     13883319.19
      3134581.11     13883451.23      3133873.19     13883715.83
      3133065.83      13884009.1      3132460.15     13884216.69
#Sta/Elev= 30
  4206.8   58.56  4316.8   59.16  4803.8   55.76  4843.8   56.56  4906.8   55.75
  4966.9   55.74  4977.1   56.24  4981.2   55.44  4991.5   47.04  4999.3   45.83
  5006.2    45.6    5021   54.97  5029.4   56.33  5128.9   56.08  5188.5   56.86
  5218.5   55.26  5318.5   56.26  5368.5   55.66  5488.5   56.16  5508.5   55.16
  5555.4   55.06  5732.8   57.06  5832.8   56.76  5942.8   55.46  6022.8   56.26
  6192.8   56.66  6422.8   56.56  6677.5   57.76  6817.5   57.66  7117.6   60.06
#Mann= 4 , 1 , 0
  4206.8      .1       0  4981.2     .04       0    5021      .1       0
  7117.6      .2       0
#XS Ineff= 2 , 0
       0  4971.2    56.4    5031       0    56.4
Permanent Ineff=
       F       F
Bank Sta=4981.2,5021
XS Rating Curve= 0
Exp/Cntr=.5,.3

Type RM Length L Ch R = 1 ,3617.5  ,354.2,357.7,449.8
BEGIN DESCRIPTION:
Cross Section 3617.5-Interpolated
END DESCRIPTION:
XS GIS Cut Line= 5
      3136216.32     13882682.72      3135698.03     13882861.77
      3134331.62     13883021.97      3133059.44     13883106.78
      3132296.16     13883756.56
#Sta/Elev= 30
  3075.6    61.6  3258.2   60.17  4031.4   59.18  4183.9    59.6  4213.9    58.4
  4273.9      60  4513.9    57.7  4683.9    58.3  4863.9    55.8  4972.7   56.33
  4979.9   54.54  4993.7   46.68  4999.8    45.9  5006.3   46.62  5030.1   55.66
  5059.7    57.2  5189.7    55.5  5209.7    56.7  5249.7    55.6  5579.7    57.2
  5809.7      55  6009.7      57  6294.7    55.7  6534.7    57.2  6784.7    55.6
  6834.7      57  7004.7    56.4  7064.7    58.1  7224.7    57.3  7277.1    59.1
#Mann= 5 , 1 , 0
  3075.6      .2       0  3258.2     .14       0  4031.4      .1       0
  4972.7     .04       0  5030.1      .1       0
Bank Sta=4972.7,5030.1
XS Rating Curve= 0
Exp/Cntr=.3,.1

Type RM Length L Ch R = 1 ,3259.8  ,63,90.3,93.6
BEGIN DESCRIPTION:
Cross Section 3259.8-Interpolated
END DESCRIPTION:
XS GIS Cut Line= 6
      3136035.27     13882679.46        3134368.     13882647.27
      3134200.62      13882685.9        3134059.     13882666.59
      3133218.49     13882638.15      3132249.72     13883657.05
#Sta/Elev= 30
  3231.3    60.2  3242.8   60.16  3965.8   58.73  4121.3    59.3  4141.3    57.4
  4201.3    58.8  4471.3      59  4841.3    55.8  4972.7   56.55  4979.9   54.76
  4993.7    46.9  4999.8   46.12  5006.3   46.84  5030.1   55.88  5038.9    54.7
  5200.7    56.1  5223.6    54.4  5293.6      56  5983.6    56.5  6304.6    56.1
  6344.6    54.7  6374.6    56.5  6514.6    55.5  6824.6    57.8  6926.9    56.7
  7074.6    57.5  7184.6    56.2  7374.6    58.6  7404.6    57.6  7460.5    59.2
#Mann= 6 , 1 , 0
  3231.3      .2       0  3242.8     .14       0  3965.8      .1       0
  4972.7     .04       0  5030.1      .1       0  6926.9      .2       0
Bank Sta=4972.7,5030.1
XS Rating Curve= 0
Exp/Cntr=.5,.3

Type RM Length L Ch R = 1 ,3169.5  ,56.4,56.4,56.4
BEGIN DESCRIPTION:
Upstream Section of Bridge/Culvert/Weir
END DESCRIPTION:
XS GIS Cut Line= 5
      3136025.08     13882652.91      3135075.48     13882619.87
      3133634.16     13882554.19      3133187.58     13882532.81
      3132183.24     13883550.77
#Sta/Elev= 30
    3230   60.09  3240.5   60.06    3450   58.89    3500   60.69    3954   58.53
    4080   57.29  4114.4   59.19  4144.4   57.39  4326.2   58.89  4446.2   57.49
  4466.2   58.79  4506.2   57.39  4972.7    56.6  4979.8   54.81  4993.7   46.95
  4999.8   46.17  5006.3   46.89    5030   55.93    5282   56.12  5378.6   54.09
  6306.1   56.59  6416.1   56.09  6446.1   54.39  6486.1   56.19  6616.1   54.99
  6656.1   56.59  6706.1   55.39  7036.1   57.69  7156.1   56.59  7500.1   59.39
#Mann= 5 , 1 , 0
    3230      .2       0  3240.5     .14       0    3954      .1       0
  4972.7     .04       0    5030      .1       0
#XS Ineff= 2 , 0
       0    4969    56.9    5039       0    56.4
Permanent Ineff=
       F       F
Bank Sta=4972.7,5030
XS Rating Curve= 0
Exp/Cntr=.5,.3