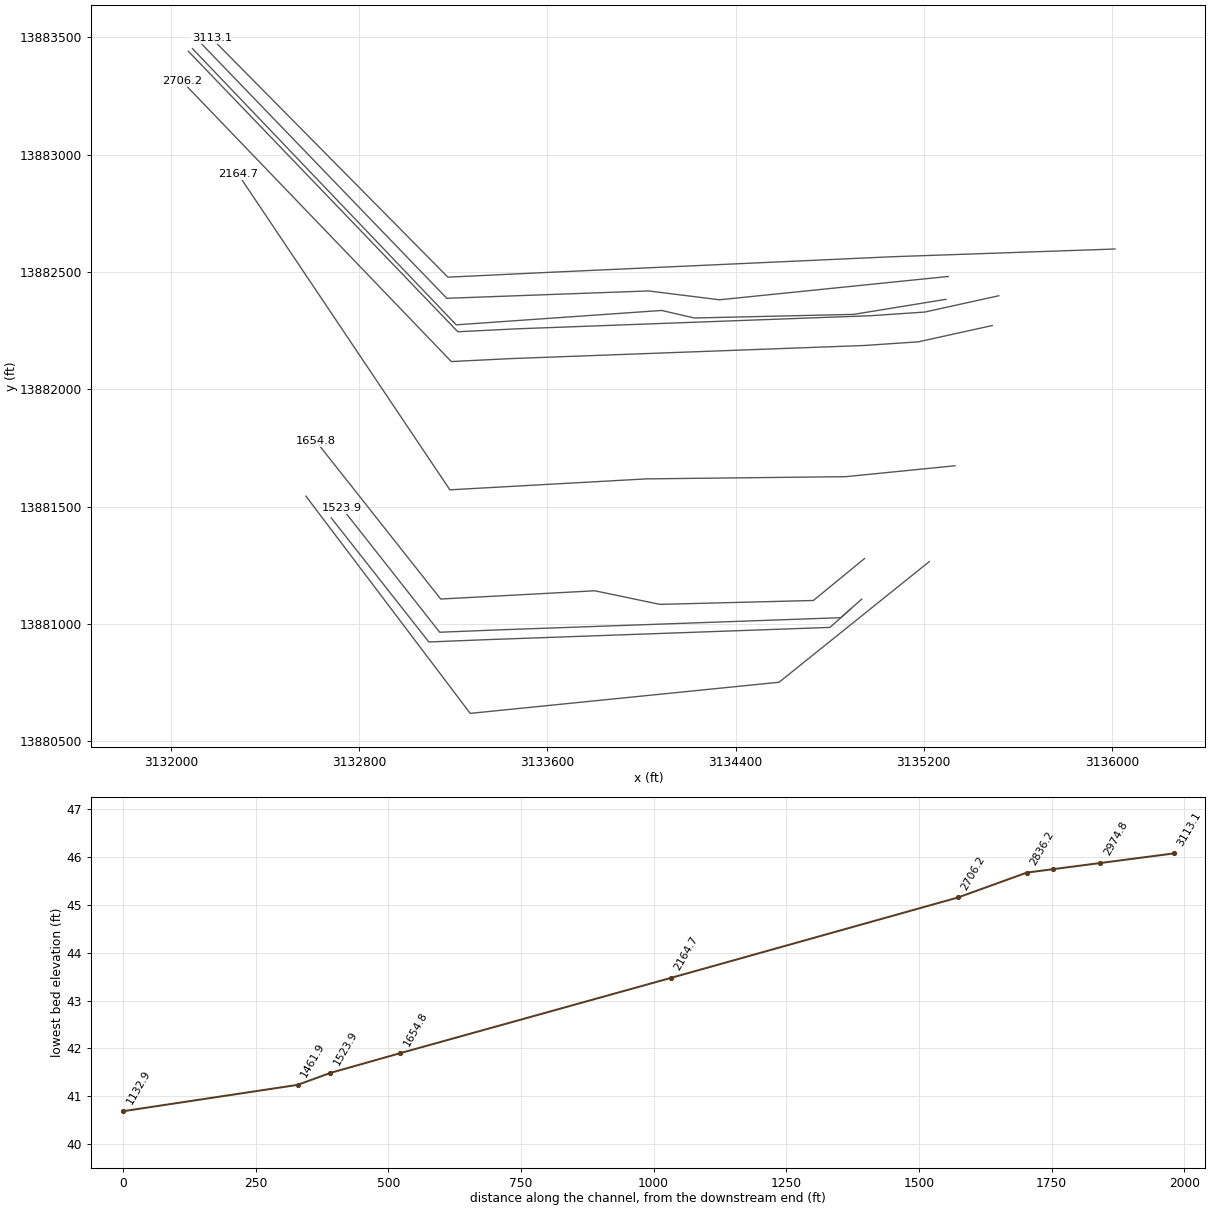
HEC-RAS study P118-14-00.PRJ: P118-14-00

--- P118-14-00.g01 (geometry) --- (continued)

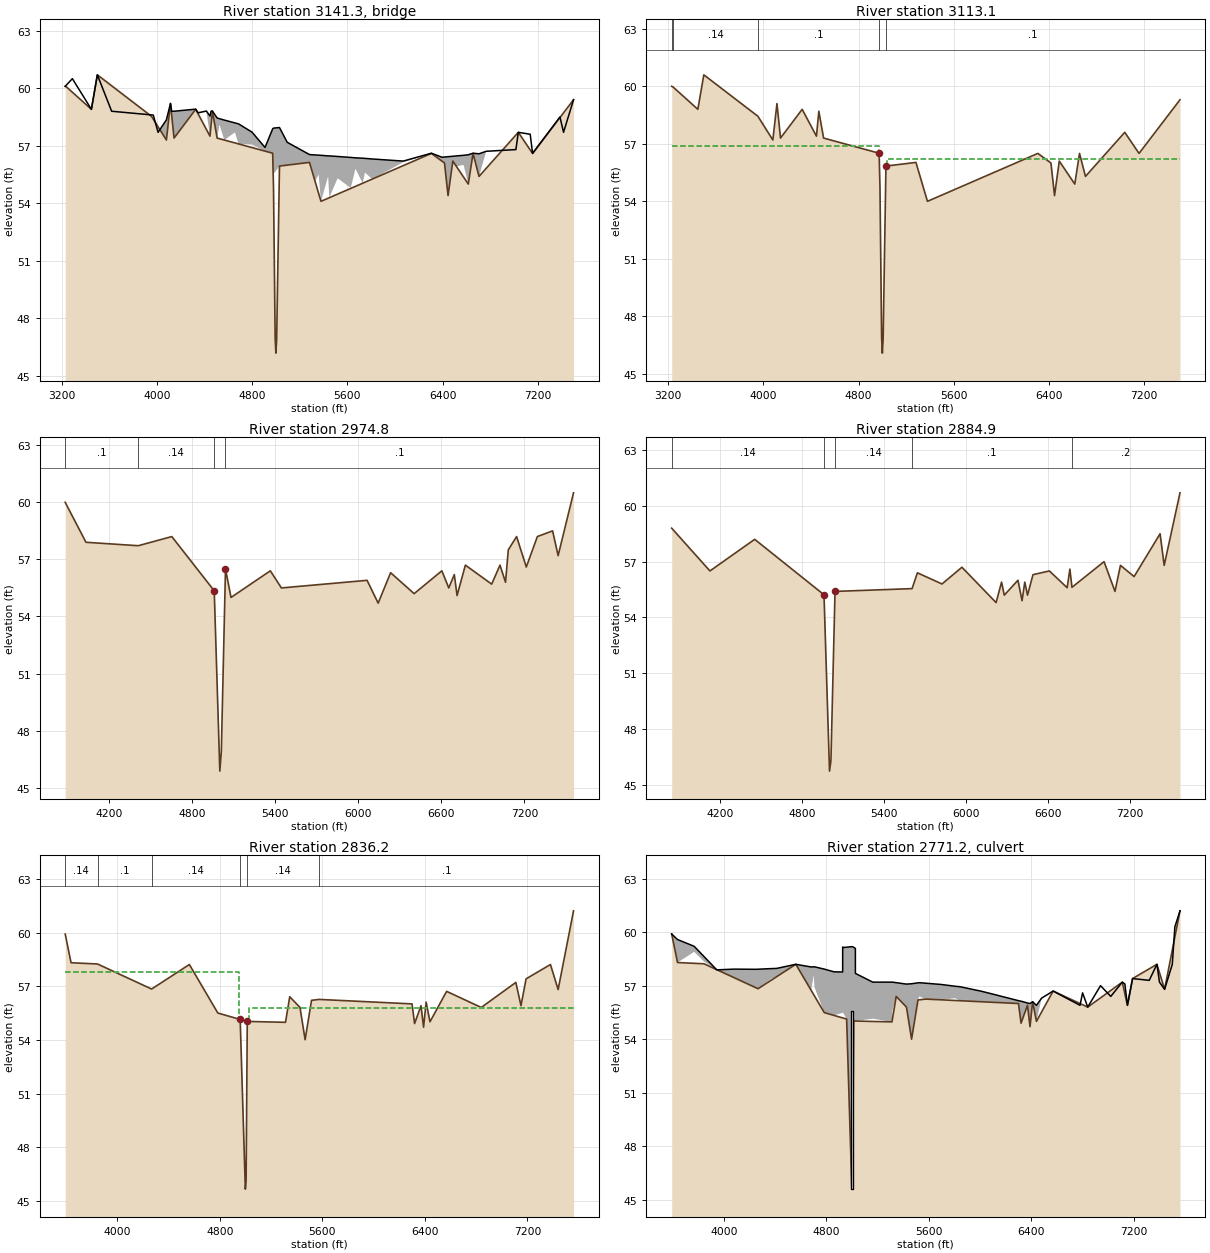
Type RM Length L Ch R = 3 ,3141.3  ,,,
BEGIN DESCRIPTION:
LITTLE CREST ROAD
Structure ID: P84-5
END DESCRIPTION:
Bridge Culvert--1,0,-1,-1, 0
Deck Dist Width WeirC Skew NumUp NumDn MinLoCord MaxHiCord MaxSubmerge Is_Ogee
10,36.4,2.6,0, 60, 60, , , .95, 0, 1,1,,
    3230    3290    3450    3500    3620    3970    4010    4080  4114.4  4124.4
  4144.4  4326.2  4346.2  4416.2  4446.2  4456.2  4466.2  4506.2  4526.2  4566.2
  4656.2  4686.2  4799.3  4908.6  4972.7 4979.91    4980    5030  5094.9    5282
  5328.6  5358.6  5378.6  5438.6  5448.6  5518.6  5628.6  5668.6  5728.6  5748.6
  5808.6    6070  6306.1  6396.1  6416.1  6446.1  6486.1  6516.1  6576.1  6616.1
  6656.1  6706.1  6766.1  7016.1  7036.1  7136.1  7156.1  7386.1  7416.1  7500.1
    60.1    60.5    58.9    60.7    58.8    58.6    57.7   58.35   59.21    58.8
    58.8   58.91   58.72   58.81   58.55   58.81   58.81   58.45   58.41   58.34
   58.19   58.14   57.71   56.91   57.88   57.92   57.92   57.95   57.18   56.54
   56.52   56.51    56.5   56.47   56.47   56.44   56.39   56.37   56.35   56.34
   56.31    56.2   56.61    56.4   56.41   56.43   56.45   56.47    56.5   56.53
   56.61   56.58   56.71    56.8    57.7    57.6    56.6    58.5    57.7    59.4
    60.1    60.5    58.9    60.7    58.8    58.6    57.7    57.3    59.2    57.8
    57.4    58.9      58    58.8    57.5    58.8    58.8    57.4    58.1    57.3
    57.7    56.7   57.06   55.95   56.61   54.76   55.52   55.94   55.26   56.13
    54.5    55.5    54.1    55.4    54.3    55.3    54.8    55.8    54.8    55.6
    54.9   56.14    56.6    55.2    56.1    54.4    56.2      55      56      55
    56.6    55.4    56.7    56.8    57.7    57.6    56.6    58.5    57.7    59.4
    3230    3290    3450    3500    3620    3970    4010    4080  4114.4  4124.4
  4144.4  4326.2  4346.2  4416.2  4446.2  4456.2  4466.2  4506.2  4526.2  4566.2
  4656.2  4686.2  4799.3  4908.6  4972.7 4979.91    4980    5030  5094.9    5282
  5328.6  5358.6  5378.6  5438.6  5448.6  5518.6  5628.6  5668.6  5728.6  5748.6
  5808.6    6070  6306.1  6396.1  6416.1  6446.1  6486.1  6516.1  6576.1  6616.1
  6656.1  6706.1  6766.1  7016.1  7036.1  7136.1  7156.1  7386.1  7416.1  7500.1
    60.1    60.5    58.9    60.7    58.8    58.6    57.7   58.35   59.21    58.8
    58.8   58.91   58.72   58.81   58.55   58.81   58.81   58.45   58.41   58.34
   58.19   58.14   57.71   56.91   57.88   57.92   57.92   57.95   57.18   56.54
   56.52   56.51    56.5   56.47   56.47   56.44   56.39   56.37   56.35   56.34
   56.31    56.2   56.61    56.4   56.41   56.43   56.45   56.47    56.5   56.53
   56.61   56.58   56.71    56.8    57.7    57.6    56.6    58.5    57.7    59.4
      60    60.4    58.8    60.6    58.7    58.5    57.6    57.2    59.1    57.7
    57.3    58.8    57.9    58.7    57.4    58.7    58.7    57.3      58    57.2
    57.6    56.6   56.96   55.85   56.51   54.66   55.42   55.84   55.16   56.03
    54.4    55.4      54    55.3    54.2    55.2    54.7    55.7    54.7    55.5
    54.8   56.04    56.5    55.1      56    54.3    56.1    54.9    55.9    54.9
    56.5    55.3    56.6    56.7    57.6    57.5    56.5    58.4    57.6    59.3
Abutment Skew #Up #Dn= , 2 , 2
  4979.8  4983.1
   55.52   52.95
  4979.8  4983.1
   55.42   52.85
Abutment Skew #Up #Dn= , 2 , 2
  5023.9 5029.29
   53.37   55.55
  5023.9 5029.29
   53.27   55.45
BR Coef= 1 , 1 , 0 ,1.25, 0 ,,,.8,0,2,0,
WSPro=,,,, 1 ,,,, 0 ,,,, 0 ,,,,-1 ,-1 ,-1 , 0 , 0 , 0 , 0 , 0
BR U #Sta/Elev= 30
    3230    60.1  3240.5   60.07    3450    58.9    3500    60.7    3954   58.54
    4080    57.3  4114.4    59.2  4144.4    57.4  4326.2    58.9  4446.2    57.5
  4466.2    58.8  4506.2    57.4  4972.7   56.61  4979.8   54.82  4993.7   46.96
  4999.8   46.18  5006.3    46.9    5030   55.94    5282   56.13  5378.6    54.1
  6306.1    56.6  6416.1    56.1  6446.1    54.4  6486.1    56.2  6616.1      55
  6656.1    56.6  6706.1    55.4  7036.1    57.7  7156.1    56.6  7500.1    59.4
BR U #Mann= 5
    3230      .2  3240.5     .14    3954      .1  4972.7     .04    5030      .1
BR U Banks=4972.7,5030
BR D #Sta/Elev= 30
    3230      60  3240.5   59.97    3450    58.8    3500    60.6    3954   58.44
    4080    57.2  4114.4    59.1  4144.4    57.3  4326.2    58.8  4446.2    57.4
  4466.2    58.7  4506.2    57.3  4972.7   56.51  4979.8   54.72  4993.7   46.86
  4999.8   46.08  5006.3    46.8    5030   55.84    5282   56.03  5378.6      54
  6306.1    56.5  6416.1      56  6446.1    54.3  6486.1    56.1  6616.1    54.9
  6656.1    56.5  6706.1    55.3  7036.1    57.6  7156.1    56.5  7500.1    59.3
BR D #Mann= 5
    3230      .2  3240.5     .14    3954      .1  4972.7     .04    5030      .1
BR D Banks=4972.7,5030
BC Design=,, 0 ,, 0 ,,,,,,

Type RM Length L Ch R = 1 ,3113.1  ,138.3,138.3,138.3
BEGIN DESCRIPTION:
Downstream Section of Bridge/Culvert/Weir
END DESCRIPTION:
XS GIS Cut Line= 5
      3136013.99     13882597.61       3135064.4     13882564.57
      3133623.08     13882498.89       3133176.5     13882477.51
      3132172.15     13883495.47
#Sta/Elev= 30
    3230   59.99  3240.5   59.96    3450   58.79    3500   60.59    3954   58.43
    4080   57.19  4114.4   59.09  4144.4   57.29  4326.2   58.79  4446.2   57.39
  4466.2   58.69  4506.2   57.29  4972.7    56.5  4979.8   54.71  4993.7   46.85
  4999.8   46.07  5006.3   46.79    5030   55.83    5282   56.02  5378.6   53.99
  6306.1   56.49  6416.1   55.99  6446.1   54.29  6486.1   56.09  6616.1   54.89
  6656.1   56.49  6706.1   55.29  7036.1   57.59  7156.1   56.49  7500.1   59.29
#Mann= 5 , 1 , 0
    3230      .2       0  3240.5     .14       0    3954      .1       0
  4972.7     .04       0    5030      .1       0
#XS Ineff= 2 , 0
       0    4969    56.9    5039       0    56.2
Permanent Ineff=
       F       F
Bank Sta=4972.7,5030
XS Rating Curve= 0
Exp/Cntr=.5,.3

Type RM Length L Ch R = 1 ,2974.8  ,79.4,89.9,108.5
BEGIN DESCRIPTION:
Cross Section 2974.8-Interpolated
END DESCRIPTION:
XS GIS Cut Line= 5
      3135304.24     13882480.56      3134331.62     13882381.17
      3134030.06     13882418.86      3133171.76     13882387.51
      3132110.39     13883491.18
#Sta/Elev= 30
  3882.6      60  4032.6    57.9  4410.2   57.72  4652.6    58.2  4959.1   55.35
  4999.4   45.87  5010.3    46.9  5040.3    56.5  5080.3      55  5364.2    56.4
  5444.2    55.5  6063.1    55.9  6143.1    54.7  6233.1    56.3  6403.1    55.2
  6603.1    56.4  6653.1    55.5  6693.1    56.2  6713.1    55.1  6773.1    56.7
  6963.1    55.7  7023.1    56.7  7063.1    55.8  7083.1    57.5  7143.1    58.2
  7213.1    56.6  7293.1    58.2  7403.1    58.5  7443.1    57.2  7554.3    60.5
#Mann= 4 , 1 , 0
  3882.6      .1       0  4410.2     .14       0  4959.1     .04       0
  5040.3      .1       0
Bank Sta=4959.1,5040.3
XS Rating Curve= 0
Exp/Cntr=.3,.1

Type RM Length L Ch R = 1 ,2884.9  ,89.6,48.7,41
BEGIN DESCRIPTION:
Cross Section 2884.9-Interpolated
END DESCRIPTION:
XS GIS Cut Line= 6
      3135294.62     13882383.17       3134902.3     13882318.97
      3134224.67     13882303.54       3134085.6     13882335.73
      3133211.91     13882274.42      3132090.49     13883451.38
#Sta/Elev= 30
  3844.4    58.8  4124.4    56.5  4451.9    58.2  4959.1   55.22  4999.4   45.74
  5009.7    46.3  5039.7    55.4  5603.5   55.55  5642.5    56.4  5822.5    55.8
  5968.3    56.7  6218.3    54.8  6258.3    55.9  6278.3    55.2  6378.3      56
  6408.3    54.9  6428.3    55.9  6448.3    55.2  6488.3    56.3  6608.3    56.5
  6738.3    55.6  6758.3    56.6  6773.4   55.62  7008.3      57  7088.3    55.4
  7128.3    56.8  7228.3    56.2  7418.3    58.5  7448.3    56.8    7564    60.7
#Mann= 5 , 1 , 0
  3844.4     .14       0  4959.1     .04       0  5039.7     .14       0
  5603.5      .1       0  6773.4      .2       0
Bank Sta=4959.1,5039.7
XS Rating Curve= 0
Exp/Cntr=.5,.3

Type RM Length L Ch R = 1 ,2836.2  ,130,130,130
BEGIN DESCRIPTION:
Upstream Section of Bridge/Culvert/Weir
END DESCRIPTION:
XS GIS Cut Line= 6
      3135519.34     13882398.31      3135205.25     13882328.99
      3134975.37     13882313.34      3133468.26     13882257.34
      3133218.81     13882244.88      3132072.55     13883440.51
#Sta/Elev= 30
  3593.8   59.92  3639.4   58.32  3845.8   58.25  4267.9   56.85  4562.5   58.22
  4784.7   55.51  4959.1   55.15  4999.4   45.67  5005.3   46.14  5014.4   55.04
  5312.7   54.99  5345.8   56.42  5425.8   55.82  5465.8   54.02  5515.8   56.22
  5575.1   56.27    6300   56.02    6320   54.92    6370   55.92    6390   54.72
    6410   56.12    6440   55.02    6570   56.72    6840   55.82    7110   57.22
    7150   55.92    7190   57.42    7380   58.22    7440   56.82  7560.1   61.22
#Mann= 6 , 1 , 0
  3593.8     .14       0  3845.8      .1       0  4267.9     .14       0
  4959.1     .04       0  5014.4     .14       0  5575.1      .1       0
#XS Ineff= 2 , 0
       0    4949    57.8    5024       0    55.8
Permanent Ineff=
       F       F
Bank Sta=4959.1,5014.4
XS Rating Curve= 0
Exp/Cntr=.5,.3

Type RM Length L Ch R = 2 ,2771.2  ,,,
BEGIN DESCRIPTION:
LITTLE YORK ROAD
Structure ID: P84-4
END DESCRIPTION:
Bridge Culvert--1,0,-1,-1, 0
Deck Dist Width WeirC Skew NumUp NumDn MinLoCord MaxHiCord MaxSubmerge Is_Ogee
10,110,3,0, 60, 60, , , .95, 0, 1,1,,
  3593.8  3639.4  3769.4  3945.4  4082.3  4252.3  4372.5  4412.5  4562.5  4682.5
  4702.5  4708.2  4784.7  4859.6 4927.89    4928    4930  4959.1    4997  4999.4
  5005.3  5014.4  5027.3 5027.41  5162.7  5312.7  5315.8  5345.8  5425.8  5465.8
  5525.8  5695.8  5805.8  5845.8    6010    6110    6300    6320    6370    6390
    6410    6440    6480    6570    6780    6800    6840    6940    7020    7110
    7130    7150    7190    7320    7380    7400    7440    7500    7520  7560.1
   59.91    59.6   59.22    57.9   57.94   57.93   57.97   57.98   58.21   58.06
   58.07   58.07   57.94   57.79   57.78   59.18   59.15   59.17    59.2    59.2
    59.2   59.16    59.1    57.7   57.21   57.21   57.21   57.18    57.1   57.12
   57.18   57.08   56.98   56.95    56.7   56.52   56.17   56.14   56.04   56.01
   56.11   55.91   56.31   56.71   55.91   56.61   55.81   57.01   56.41   57.21
   57.11   55.91   57.41   57.31   58.21   57.21   56.81   58.21   60.31   61.21
   59.91   58.31   58.91   57.66   56.51   56.51   57.41   56.91   58.21   56.71
   57.61   56.92    55.5   54.93   55.49   55.49   55.51   55.14   45.67   45.66
   46.13   55.03   54.86   54.86   55.16   54.98   55.61   56.41   55.81   54.01
   56.41   55.41   56.31   55.61   56.11   55.21   56.01   54.91   55.91   54.71
   56.11   55.01   56.31   56.71   55.91   56.61   55.81   57.01   56.41   57.21
   57.11   55.91   57.41   57.31   58.21   57.21   56.81   58.21   60.31   61.21
  3593.8  3639.4  3769.4  3945.4  4082.3  4252.3  4372.5  4412.5  4442.5  4562.5
  4682.5  4702.5  4708.2  4784.7  4859.6 4927.89    4928    4930  4959.1    4997
  4999.4  5005.3  5014.4  5027.3 5027.41  5162.7  5312.7  5345.8  5425.8  5465.8
  5525.8  5695.8  5805.8  5845.8    6010    6110    6300    6320    6370    6390
    6410    6440    6480    6570    6780    6800    6840    6940    7020    7110
    7130    7150    7190    7320    7380    7400    7440    7500    7520  7560.1
    59.7    59.6   59.22    57.9   57.94   57.93   57.97   57.98   57.99   58.03
   58.06   58.07   58.07   57.94   57.79   57.78   59.18   59.15   59.17    59.2
    59.2    59.2   59.16    59.1    57.7   57.21   57.21   57.18    57.1   57.12
   57.18   57.08   56.98   56.95    56.7   56.52   56.17   56.14   56.04   56.01
   55.97   55.91   56.11   56.51    55.7    56.4    55.6    56.8    56.2      57
    56.9    55.7    57.2    57.1      58      57    56.6      58    60.1      61
   59.43   57.83   58.43   57.18   56.03   56.03   56.93   56.43   57.23   57.73
   56.23   57.13   56.44   55.02   54.45   55.01   55.01   55.03   54.66   45.19
   45.18   45.65   54.55   54.38   54.38   54.68    54.5   55.93   55.33   53.53
   55.93   54.93   55.83   55.13   55.63   54.73   55.53   54.43   55.43   54.23
   55.63   54.53   55.83   56.23   55.43   56.13   55.33   56.53   55.93   56.73
   56.63   55.43   56.93   56.83   57.73   56.73   56.33   57.73   59.83   60.73
BR Coef= 1 , 0 , 0 ,1.25, 0 ,,,.8,-1,2,0,
WSPro=,,,, 1 ,,,, 0 ,,,, 0 ,,,,-1 ,-1 ,-1 , 0 , 0 , 0 , 0 , 0
Culvert=2,10,10,110,.015,.4,1,8,1,45.6,5000.5,45.3,5000.5,Culvert #1  , 0 ,10
Culvert Bottom n=.015
BR U #Sta/Elev= 30
  3593.8   59.91  3639.4   58.31  3845.8   58.24  4267.9   56.84  4562.5   58.21
  4784.7    55.5  4959.1   55.14  4999.4   45.66  5005.3   46.13  5014.4   55.03
  5312.7   54.98  5345.8   56.41  5425.8   55.81  5465.8   54.01  5515.8   56.21
  5575.1   56.26    6300   56.01    6320   54.91    6370   55.91    6390   54.71
    6410   56.11    6440   55.01    6570   56.71    6840   55.81    7110   57.21
    7150   55.91    7190   57.41    7380   58.21    7440   56.81  7560.1   61.21
BR U #Mann= 6
  3593.8     .14  3845.8      .1  4267.9     .14  4959.1     .04  5014.4     .14
  5575.1      .1
BR U Banks=4959.1,5014.4
BR D #Sta/Elev= 30
  3593.8   59.43  3639.4   57.83  3845.8   57.76  4267.9   56.36  4562.5   57.73
  4784.7   55.02  4959.1   54.66  4999.4   45.18  5005.3   45.65  5014.4   54.55
  5312.7    54.5  5345.8   55.93  5425.8   55.33  5465.8   53.53  5515.8   55.73
  5575.1   55.78    6300   55.53    6320   54.43    6370   55.43    6390   54.23
    6410   55.63    6440   54.53    6570   56.23    6840   55.33    7110   56.73
    7150   55.43    7190   56.93    7380   57.73    7440   56.33  7560.1   60.73
BR D #Mann= 6
  3593.8     .14  3845.8      .1  4267.9     .14  4959.1     .04  5014.4     .14
  5575.1      .1
BR D Banks=4959.1,5014.4
BC Design=,, 0 ,, 0 ,,,,,,

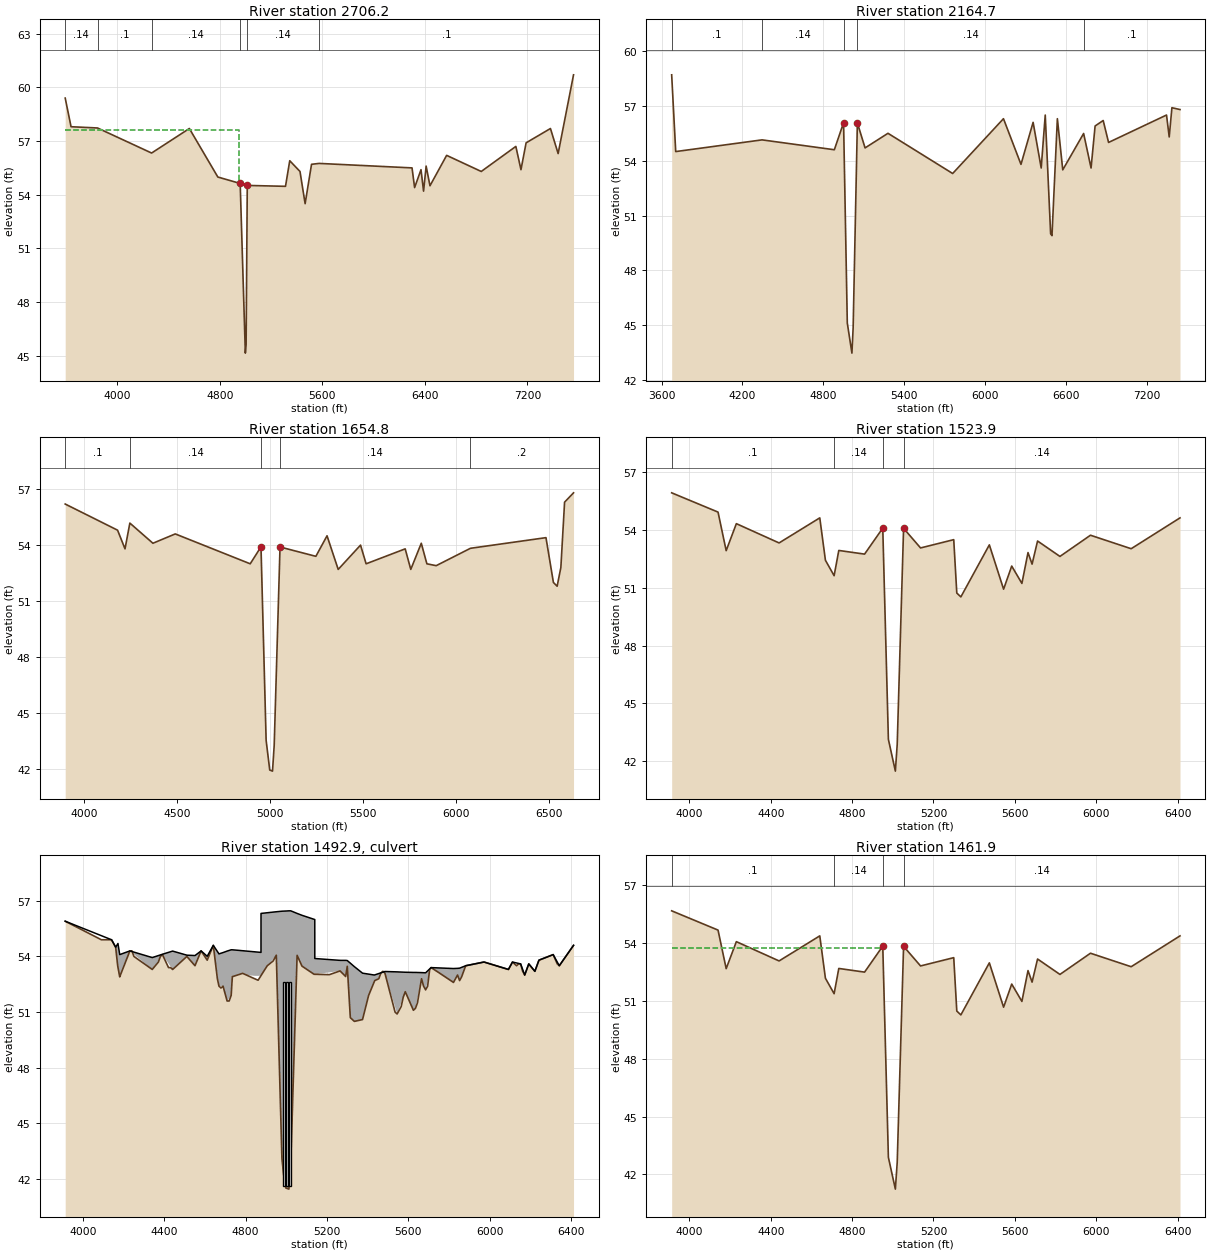
Type RM Length L Ch R = 1 ,2706.2  ,541.5,541.5,541.5
BEGIN DESCRIPTION:
Downstream Section of Bridge/Culvert/Weir
END DESCRIPTION:
XS GIS Cut Line= 6
      3135491.52     13882271.32      3135177.43     13882202.01
      3134947.55     13882186.36      3133440.44     13882130.36
      3133190.99      13882117.9      3132044.74     13883313.52
#Sta/Elev= 30
  3593.8    59.4  3639.4    57.8  3845.8   57.73  4267.9   56.33  4562.5    57.7
  4784.7   54.99  4959.1   54.63  4999.4   45.15  5005.3   45.62  5014.4   54.52
  5312.7   54.47  5345.8    55.9  5425.8    55.3  5465.8    53.5  5515.8    55.7
  5575.1   55.75    6300    55.5    6320    54.4    6370    55.4    6390    54.2
    6410    55.6    6440    54.5    6570    56.2    6840    55.3    7110    56.7
    7150    55.4    7190    56.9    7380    57.7    7440    56.3  7560.1    60.7
#Mann= 6 , 1 , 0
  3593.8     .14       0  3845.8      .1       0  4267.9     .14       0
  4959.1     .04       0  5014.4     .14       0  5575.1      .1       0
#XS Ineff= 2 , 0
       0    4949    57.6    5024       0    53.3
Permanent Ineff=
       F       F
Bank Sta=4959.1,5014.4
XS Rating Curve= 0
Exp/Cntr=.5,.3

Type RM Length L Ch R = 1 ,2164.7  ,519.3,509.9,500.5
BEGIN DESCRIPTION:
Cross Section 2164.7-Interpolated
END DESCRIPTION:
XS GIS Cut Line= 5
      3135333.54     13881673.77      3134868.76     13881627.29
      3134020.64     13881617.86      3133184.96     13881571.22
      3132283.86     13882917.42
#Sta/Elev= 30
    3675    58.7    3705    54.5  4345.8   55.14  4882.1    54.6  4950.7   56.08
  4978.3   45.12  5012.6   43.47  5021.7   44.86    5053   56.07  5110.2    54.7
  5280.2    55.5  5760.2    53.3  6137.2    56.3  6267.2    53.8  6357.2    56.1
  6417.2    53.6  6447.2    56.5  6487.2      50  6497.2    49.9  6537.2    56.3
  6577.2    53.5    6732   55.49  6787.2    53.6  6817.2    55.9  6877.2    56.2
  6917.2      55  7347.2    56.5  7367.2    55.3  7387.2    56.9  7447.2    56.8
#Mann= 5 , 1 , 0
    3675      .1       0  4345.8     .14       0  4950.7     .04       0
    5053     .14       0    6732      .1       0
Bank Sta=4950.7,5053
XS Rating Curve= 0
Exp/Cntr=.3,.1

Type RM Length L Ch R = 1 ,1654.8  ,91.6,130.9,123.9
BEGIN DESCRIPTION:
Cross Section 1654.8-Interpolated
END DESCRIPTION:
XS GIS Cut Line= 6
      3134948.43     13881278.19      3134730.94     13881099.62
      3134078.31     13881082.99      3133801.51     13881140.93
      3133145.93     13881105.73      3132614.62     13881779.48
#Sta/Elev= 30
  3898.6    56.2    4180    54.8    4220    53.8    4246   55.18    4370    54.1
    4490    54.6  4892.8      53  4950.7   53.91  4978.3   43.55  4997.7   41.96
  5012.6    41.9  5021.7   43.29    5053    53.9  5245.6    53.4  5305.6    54.5
  5365.6    52.7  5485.6      54  5515.6      53  5725.6    53.8  5755.6    52.7
  5812.1    54.1  5842.1      53  5892.1    52.9  6076.2   53.83  6482.1    54.4
  6522.1      52  6542.1    51.8  6562.1    52.8  6582.1    56.3  6630.2    56.8
#Mann= 5 , 1 , 0
  3898.6      .1       0    4246     .14       0  4950.7     .04       0
    5053     .14       0  6076.2      .2       0
Bank Sta=4950.7,5053
XS Rating Curve= 0
Exp/Cntr=.5,.3

Type RM Length L Ch R = 1 ,1523.9  ,62,62,62
BEGIN DESCRIPTION:
Upstream Section of Bridge/Culvert/Weir
END DESCRIPTION:
XS GIS Cut Line= 5
      3134936.62     13881105.38      3134847.34     13881026.31
      3133397.72     13880974.47      3133141.62     13880964.26
      3132726.44     13881492.91
#Sta/Elev= 30
  3913.2   55.93  4141.1   54.93  4181.1   52.93  4231.1   54.33  4441.1   53.33
  4641.1   54.63  4668.9   52.43  4711.6   51.63  4734.6   52.94  4861.3   52.75
  4950.7    54.1  4978.3   43.14  5012.6   41.49  5021.7   42.88    5053   54.09
  5136.4   53.07  5299.5    53.5  5314.5   50.73  5334.5   50.53  5474.5   53.23
  5544.5   50.93  5584.5   52.13  5634.5   51.23  5664.5   52.83  5684.5   52.23
  5711.5   53.43  5821.5   52.63  5971.5   53.73  6171.5   53.03  6411.5   54.63
#Mann= 4 , 1 , 0
  3913.2      .1       0  4711.6     .14       0  4950.7     .04       0
    5053     .14       0
#XS Ineff= 2 , 0
       0    4940    53.8  5062.6       0    53.3
Permanent Ineff=
       F       F
Bank Sta=4950.7,5053
XS Rating Curve= 0
Exp/Cntr=.5,.3

Type RM Length L Ch R = 2 ,1492.9  ,,,
BEGIN DESCRIPTION:
LANGLEY ROAD
Structure ID: P84-2
END DESCRIPTION:
Bridge Culvert--1,0,-1,-1, 0
Deck Dist Width WeirC Skew NumUp NumDn MinLoCord MaxHiCord MaxSubmerge Is_Ogee
10,42,3,0, 60, 60, , , .95, 0, 1,1,,
  3913.2  4141.1  4161.1  4172.5  4181.1  4231.1  4341.1  4391.1  4441.1  4511.1
  4551.1  4581.1  4611.1  4641.1  4668.9  4688.9  4708.9  4728.9  4734.6 4875.39
  4875.5  4950.7  4978.3  4997.7  5012.6  5021.7    5053  5076.8  5139.8 5139.91
  5264.1  5291.5  5299.5  5314.5  5334.5  5374.5  5432.5  5484.5  5544.5  5584.5
  5624.5  5634.5  5664.5  5684.5  5711.5  5821.5  5841.5  5851.5  5881.5  5971.5
  6091.5  6111.5  6151.5  6171.5  6191.5  6221.5  6241.5  6311.5  6341.5  6411.5
    55.9    54.9    54.5    54.7    54.1    54.3   53.94   54.12   54.29   54.07
   54.05    54.3   54.01    54.6   54.14   54.21   54.29   54.36   54.36   54.22
   56.32   56.41   56.44   56.45   56.46   56.46   56.32   56.22   55.99   53.89
   53.79   53.79   53.78   53.64   53.45    53.1      53   53.19   53.17   53.15
   53.14   53.14   53.13   53.12    53.4   53.35   53.36   53.37    53.5    53.7
    53.3    53.7    53.6      53    53.6    53.2    53.8    54.1    53.5    54.6
    55.9    54.9    54.5   53.42    52.9    54.3    53.3    54.1    53.3      54
    53.5    54.3    53.8    54.6    52.4    52.4    51.6    51.9   52.91   52.96
   52.97   54.07   43.11   41.52   41.46   42.85   54.06   53.48   53.04   53.04
   53.22   52.92   53.47    50.7    50.5    50.6   52.65    53.1    50.9    52.1
    51.1    51.2    52.8    52.2    53.4    52.6      53    52.7    53.5    53.7
    53.3    53.7    53.6      53    53.6    53.2    53.8    54.1    53.5    54.6
  3913.2  4141.1  4161.1  4172.5  4181.1  4231.1  4341.1  4391.1  4441.1  4511.1
  4551.1  4581.1  4611.1  4641.1  4668.9  4688.9  4708.9  4728.9  4734.6 4875.39
  4875.5  4950.7  4978.3  4997.7  5012.6  5021.7    5053  5076.8  5139.8 5139.91
  5264.1  5291.5  5299.5  5314.5  5334.5  5374.5  5432.5  5474.5  5544.5  5584.5
  5624.5  5634.5  5664.5  5684.5  5711.5  5821.5  5841.5  5851.5  5881.5  5971.5
  6091.5  6111.5  6151.5  6171.5  6191.5  6221.5  6241.5  6311.5  6341.5  6411.5
    55.8   54.81   54.46    54.7    54.1   54.21   53.94   54.12   54.29   54.07
   54.05   54.21   54.01   54.51   54.14   54.21   54.29   54.36   54.36   54.22
   56.32   56.41   56.44   56.45   56.46   56.46   56.32   56.22   55.99   53.89
   53.79   53.79   53.78   53.64   53.45    53.1      53   53.19   53.17   53.15
   53.14   53.14   53.13   53.12   53.31   53.35   53.36   53.37   53.41    53.6
    53.2    53.6    53.5    52.9    53.5    53.1    53.7      54    53.4    54.5
    55.7    54.7    54.3   53.22    52.7    54.1    53.1    53.9    53.1    53.8
    53.3    54.1    53.6    54.4    52.2    52.2    51.4    51.7   52.71   52.76
   52.77   53.87   42.91   41.32   41.26   42.65   53.86   53.28   52.84   52.84
   53.02   52.72   53.27    50.5    50.3    50.4   52.45      53    50.7    51.9
    50.9      51    52.6      52    53.2    52.4    52.8    52.5    53.3    53.5
    53.1    53.5    53.4    52.8    53.4      53    53.6    53.9    53.3    54.4
BR Coef= 1 , 0 , 0 ,1.25, 0 ,,,.8,-1,2,0,
WSPro=,,,, 1 ,,,, 0 ,,,, 0 ,,,,-1 ,-1 ,-1 , 0 , 0 , 0 , 0 , 0
Culvert=2,11,9,42,.015,.4,1,8,1,41.64,4988.2,41.34,4988.2,Culvert #1  , 0 ,10
Culvert Bottom n=.015
Culvert=2,11,9,42,.015,.4,1,8,1,41.64,5001.6,41.34,5001.6,Culvert #2  , 0 ,10
Culvert Bottom n=.015
Culvert=2,11,9,42,.015,.4,1,8,1,41.64,5016.1,41.34,5016.1,Culvert #3  , 0 ,10
Culvert Bottom n=.015
BR U #Sta/Elev= 131
  3913.2    55.9  4025.4   55.27  4032.5   55.23  4052.5   55.12  4062.5   55.06
  4091.1    54.9  4141.1    54.9  4152.5   54.67  4161.1    54.5  4162.5   54.36
  4171.1    53.5  4172.5   53.42  4181.1    52.9  4182.5   52.94  4231.1    54.3
  4232.5    54.3  4241.1    54.3  4242.5   54.26  4251.1      54  4302.5    53.6
  4341.1    53.3  4371.1    53.7  4381.1      54  4391.1    54.1  4421.1    53.4
  4431.1    53.4  4441.1    53.3  4442.5   53.31  4452.5   53.41  4511.1      54
  4551.1    53.5  4581.1    54.3  4611.1    53.8  4632.5   54.37  4641.1    54.6
  4661.1    52.8  4668.9    52.4  4678.9    52.3  4688.9    52.4  4708.9    51.6
  4711.6    51.6  4718.9    51.6  4728.5   51.89  4728.9    51.9  4734.6   52.91
  4734.7   52.91  4785.3   53.09  4805.4   52.99  4852.5   52.76  4861.3   52.72
 4875.39   52.96  4875.5   52.97 4875.61   52.97  4893.5   53.28  4906.3    53.5
  4935.4   53.76  4950.7   54.07  4955.6   52.12  4978.3   43.11  4986.8   42.23
  4997.7   41.52  5012.6   41.46  5020.1   42.61  5021.7   42.85 5052.09   53.73
  5052.2   53.77 5052.31   53.81    5053   54.06  5067.1   53.72  5076.8   53.48
  5136.4   53.04  5139.6   53.04 5139.69   53.04  5139.8   53.04 5139.91   53.04
  5197.2   53.02  5211.4   53.02  5264.1   53.22  5291.5   52.92  5298.4   53.39
  5299.5   53.47  5314.5    50.7  5334.5    50.5  5372.5    50.6  5374.5    50.6
  5404.5    51.9  5432.5   52.65  5434.5    52.7  5442.5   52.74  5454.5    52.8
  5464.5    53.1  5474.5    53.2  5484.5    53.1  5534.5      51  5544.5    50.9
  5564.5    51.3  5574.5    51.8  5584.5    52.1  5624.5    51.1  5634.5    51.2
  5644.5    51.5  5664.5    52.8  5674.5    52.4  5684.5    52.2  5694.5    52.4
  5704.5    53.3  5711.5    53.4  5739.3    53.2  5749.3   53.13  5821.5    52.6
  5841.5      53  5851.5    52.7  5861.5    52.9  5881.5    53.5  5899.3   53.54
  5971.5    53.7  6091.5    53.3  6111.5    53.7  6131.5    53.5  6141.5    53.6
  6151.5    53.6  6161.5    53.2  6171.5      53  6191.5    53.6  6221.5    53.2
  6231.5    53.5  6241.5    53.8  6311.5    54.1  6331.5    53.6  6341.5    53.5
  6411.5    54.6
BR U #Mann= 4
  3913.2      .1  4711.6     .14  4950.7     .04    5053     .14
BR U Banks=4950.7,5053
BR D #Sta/Elev= 131
  3913.2    55.7  4025.4   55.07  4032.5   55.03  4052.5   54.92  4062.5   54.86
  4091.1    54.7  4141.1    54.7  4152.5   54.47  4161.1    54.3  4162.5   54.16
  4171.1    53.3  4172.5   53.22  4181.1    52.7  4182.5   52.74  4231.1    54.1
  4232.5    54.1  4241.1    54.1  4242.5   54.06  4251.1    53.8  4302.5    53.4
  4341.1    53.1  4371.1    53.5  4381.1    53.8  4391.1    53.9  4421.1    53.2
  4431.1    53.2  4441.1    53.1  4442.5   53.11  4452.5   53.21  4511.1    53.8
  4551.1    53.3  4581.1    54.1  4611.1    53.6  4632.5   54.17  4641.1    54.4
  4661.1    52.6  4668.9    52.2  4678.9    52.1  4688.9    52.2  4708.9    51.4
  4711.6    51.4  4718.9    51.4  4728.5   51.69  4728.9    51.7  4734.6   52.71
  4734.7   52.71  4785.3   52.89  4805.4   52.79  4852.5   52.56  4861.3   52.52
 4875.39   52.76  4875.5   52.77 4875.61   52.77  4893.5   53.08  4906.3    53.3
  4935.4   53.56  4950.7   53.87  4955.6   51.92  4978.3   42.91  4986.8   42.03
  4997.7   41.32  5012.6   41.26  5020.1   42.41  5021.7   42.65 5052.09   53.53
  5052.2   53.57 5052.31   53.61    5053   53.86  5067.1   53.52  5076.8   53.28
  5136.4   52.84  5139.6   52.84 5139.69   52.84  5139.8   52.84 5139.91   52.84
  5197.2   52.82  5211.4   52.82  5264.1   53.02  5291.5   52.72  5298.4   53.19
  5299.5   53.27  5314.5    50.5  5334.5    50.3  5372.5    50.4  5374.5    50.4
  5404.5    51.7  5432.5   52.45  5434.5    52.5  5442.5   52.54  5454.5    52.6
  5464.5    52.9  5474.5      53  5484.5    52.9  5534.5    50.8  5544.5    50.7
  5564.5    51.1  5574.5    51.6  5584.5    51.9  5624.5    50.9  5634.5      51
  5644.5    51.3  5664.5    52.6  5674.5    52.2  5684.5      52  5694.5    52.2
  5704.5    53.1  5711.5    53.2  5739.3      53  5749.3   52.93  5821.5    52.4
  5841.5    52.8  5851.5    52.5  5861.5    52.7  5881.5    53.3  5899.3   53.34
  5971.5    53.5  6091.5    53.1  6111.5    53.5  6131.5    53.3  6141.5    53.4
  6151.5    53.4  6161.5      53  6171.5    52.8  6191.5    53.4  6221.5      53
  6231.5    53.3  6241.5    53.6  6311.5    53.9  6331.5    53.4  6341.5    53.3
  6411.5    54.4
BR D #Mann= 4
  3913.2      .1  4711.6     .14  4950.7     .04    5053     .14
BR D Banks=4950.7,5053
BC Design=,, 0 ,, 0 ,,,,,,

Type RM Length L Ch R = 1 ,1461.9  ,329,329,329
BEGIN DESCRIPTION:
Downstream Section of Bridge/Culvert/Weir
END DESCRIPTION:
XS GIS Cut Line= 5
      3134890.55     13881063.89      3134801.26     13880984.83
      3133351.64     13880932.99      3133095.54     13880922.78
      3132680.37     13881451.42
#Sta/Elev= 30
  3913.2   55.68  4141.1   54.68  4181.1   52.68  4231.1   54.08  4441.1   53.08
  4641.1   54.38  4668.9   52.18  4711.6   51.38  4734.6   52.69  4861.3    52.5
  4950.7   53.85  4978.3   42.89  5012.6   41.24  5021.7   42.63    5053   53.84
  5136.4   52.82  5299.5   53.25  5314.5   50.48  5334.5   50.28  5474.5   52.98
  5544.5   50.68  5584.5   51.88  5634.5   50.98  5664.5   52.58  5684.5   51.98
  5711.5   53.18  5821.5   52.38  5971.5   53.48  6171.5   52.78  6411.5   54.38
#Mann= 4 , 1 , 0
  3913.2      .1       0  4711.6     .14       0  4950.7     .04       0
    5053     .14       0
#XS Ineff= 2 , 0
       0    4940   53.73  5062.6       0    53.3
Permanent Ineff=
       F       F
Bank Sta=4950.7,5053
XS Rating Curve= 0
Exp/Cntr=.5,.3

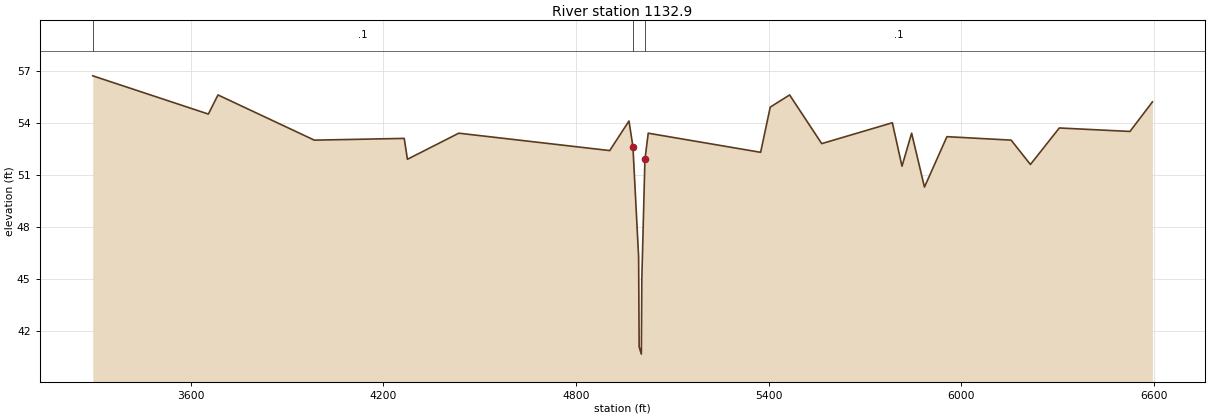
Type RM Length L Ch R = 1 ,1132.9  ,0,0,0
BEGIN DESCRIPTION:
Cross Section XS01-Interpolated
END DESCRIPTION:
XS GIS Cut Line= 4
      3135223.91      13881265.2      3134585.07     13880751.13
      3133271.43     13880618.44      3132572.65     13881544.33
#Sta/Elev= 30
    3295    56.7    3655    54.5    3685    55.6    3985      53    4265    53.1
    4275    51.9    4435    53.4    4905    52.4    4965    54.1  4977.3   52.63
    4995    46.3  4996.7   41.11  5003.5   40.69    5005      45  5014.7   51.89
    5025    53.4    5375    52.3    5405    54.9  5465.3    55.6  5565.3    52.8
  5785.3      54  5815.3    51.5  5845.3    53.4  5885.3    50.3  5955.3    53.2
  6155.3      53  6215.3    51.6  6305.3    53.7  6525.3    53.5  6595.3    55.2
#Mann= 3 , 0 , 0
    3295      .1       0  4977.3     .04       0  5014.7      .1       0
Bank Sta=4977.3,5014.7
XS Rating Curve= 0
Exp/Cntr=.3,.1

Chan Stop Cuts=-1